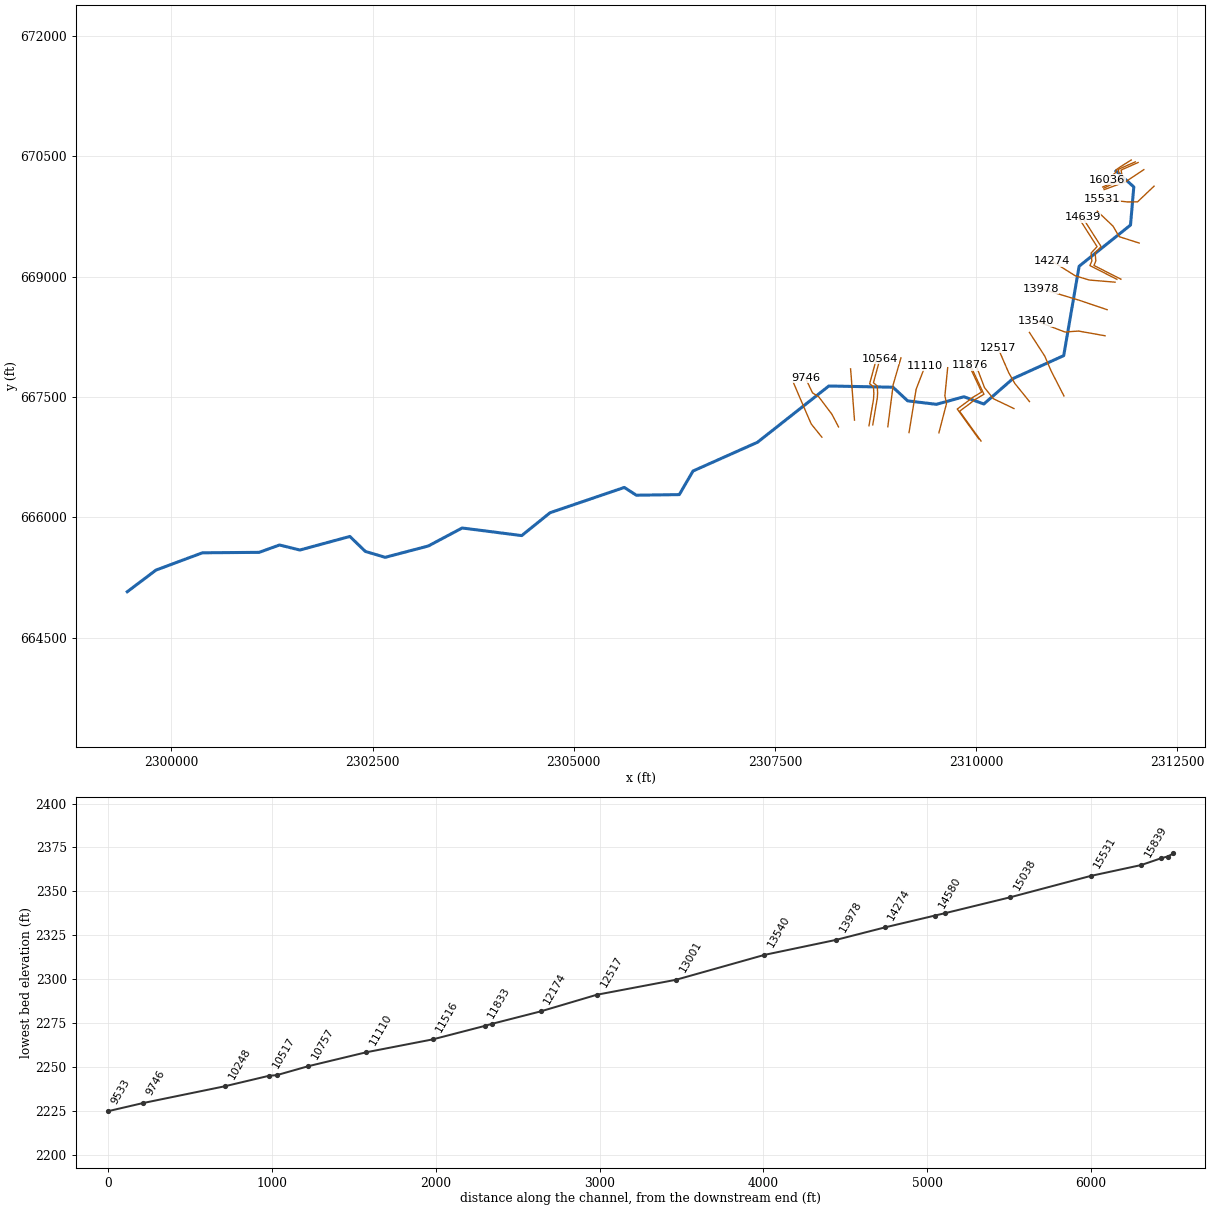
--- LFFILESCK.prj (project) ---

Proj Title=LFFILESCK
Current Plan=p01
Default Exp/Contr=0,0
English Units
Geom File=g01
Flow File=f01
Plan File=p01
BEGIN DESCRIPTION:
----------MODEL BY WOOD PLC 2022----------
AFH study
Randolph County, WV
HEC-RAS Version: RAS 6.2
Vertical Datum: NAVD88
Projection: NAD 1983 StatePlane West Virginia S FIPS 4702 (US Feet)
Terrain: 1-meter LIDAR (FEMA Region III 3DEP collected 2016-2018)
Land Use: 2019 NLCD
Hydrologic Method:
WV SIR2010-5033 regression equations
Additional Model Notes:
Main stem is FILESCK/RFFILESCK
END DESCRIPTION:
DSS Export Rating Curves= 0
DSS Export Rating Curve Sorted= 0
DSS Export Volume Flow Curves= 0
DXF OffsetX= 0
DXF OffsetY= 0
DXF ScaleX= 0
DXF ScaleY= 0

--- LFFILESCK.p01 (plan) ---

Plan Title=Floodplain
Program Version=6.20
Short Identifier=Floodplain
Geom File=g01
Flow File=f01
Subcritical Flow
K Sum by GR= 0
Std Step Tol= 0.01
Critical Tol= 0.01
Num of Std Step Trials= 20
Max Error Tol= 0.3
Flow Tol Ratio= 0.001
Split Flow NTrial= 30
Split Flow Tol= 0.02
Split Flow Ratio= 0.02
Log Output Level= 0
Friction Slope Method= 1
Unsteady Friction Slope Method= 2
Unsteady Bridges Friction Slope Method= 1
Parabolic Critical Depth
Global Vel Dist= 0 , 0 , 0
Global Log Level= 0
CheckData=True
Encroach Param=-1 ,0,0, 0
Mapping Interval=1HOUR
Computation Time Step Use Courant=        0
Computation Time Step Use Time Series=    0
Computation Time Step Count To Double=0
Computation Time Step Max Doubling=0
Computation Time Step Max Halving=0
Computation Time Step Residence Courant=0
Run HTab= 0
Run UNet= 0
Run Sediment= 0
Run PostProcess= 0
Run WQNet= 0
Run RASMapper=-1
UNET Theta= 0
UNET Theta Warmup= 0
UNET ZTol= 0
UNET ZSATol= 0
UNET MxIter= 0
UNET Max Iter WO Improvement= 0
UNET MaxInSteps= 0
UNET DtIC= 0
UNET DtMin= 0
UNET MaxCRTS= 0
UNET WFStab= 0
UNET SFStab= 0
UNET WFX= 1
UNET SFX= 1
UNET Gravity=32.174
UNET 1D Methodology=Finite Difference
UNET DSS MLevel= 1
UNET Pardiso=0
UNET DZMax Abort= 0
UNET Use Existing IB Tables= 0
UNET Froude Reduction=False
UNET Froude Limit= 0
UNET Froude Power= 0
UNET D1 Cores= 0
UNET WindReference=Eulerian
UNET WindDragFormulation=Hsu (1988)
UNET D2 Coriolis=0
UNET D2 Cores= 0
UNET D2 Theta= 1
UNET D2 Theta Warmup= 1
UNET D2 Z Tol= 0.01
UNET D2 Volume Tol= 0.01
UNET D2 Max Iterations= 20
UNET D2 Equation= 0
UNET D2 RampUpFraction=0.1
UNET D2 TimeSlices= 1
UNET D2 Turbulence Formulation=Non-Conservative (original)
UNET D2 Eddy Viscosity=0.3
UNET D2 Transverse Eddy Viscosity=0.1
UNET D2 Smagorinsky Mixing=0
UNET D2 BCVolumeCheck=0
UNET D2 Cores=0
UNET D2 SolverType=PARDISO (Direct)
UNET D2 Minimum Iterations= 2147483647
UNET D2 Maximum Iterations= 2147483647
UNET D2 Restart Number= 10
UNET D2 Relaxation Coeff=1.3
UNET D2 SOR Precondition Iterations= 10
UNET D2 ILUT Maximum Fill= 8
UNET D2 ILUT Tolerance=1E-08
UNET D1D2 MaxIter= 0
UNET D1D2 ZTol=0.01
UNET D1D2 QTol=0.1
UNET D1D2 MinQTol=1
Write IC File= 0
Write IC File at Fixed DateTime=0
Write IC File at Sim End=0
Echo Input=False
Echo Parameters=False
Echo Output=False
Write Detailed= 0
HDF Write Warmup=0
HDF Write Time Slices=0
HDF Flush=0
HDF Compression= 1
HDF Chunk Size= 1
HDF Spatial Parts= 1
HDF Use Max Rows=0
HDF Fixed Rows= 1
Calibration Method= 0
Calibration Iterations= 20
Calibration Max Change=0.05
Calibration Tolerance=0.2
Calibration Maximum=1.5
Calibration Minimum=0.5
Calibration Optimization Method= 1
WQ AD Non Conservative
WQ ULTIMATE=-1
WQ Max Comp Step=1HOUR
WQ Output Interval=15MIN
WQ Output Selected Increments= 0
WQ Output face flow=0
WQ Output face velocity=0
WQ Output face area=0
WQ Output face dispersion=0
WQ Output cell volume=0
WQ Output cell surface area=0
WQ Output cell continuity=0
WQ Output cumulative cell continuity=0
WQ Output face conc=0
WQ Output face dconc_dx=0
WQ Output face courant=0
WQ Output face peclet=0
WQ Output face adv mass=0
WQ Output face disp mass=0
WQ Output cell mass=0
WQ Output cell source sink temp=0
WQ Output nsm pathways=0
WQ Output nsm derived pathways=0
WQ Create Restart=0
WQ Fixed Restart=0
WQ System Summary=0
WQ Write To DSS=0
Sorting and Armoring Iterations= 10
XS Update Threshold= 0.02
Bed Roughness Predictor= 0
Hydraulics Update Threshold= 0.02
Energy Slope Method= 1
Volume Change Method= 1
Sediment Retention Method= 0
Sediment TS Multiplier= 1
Warm Up Method= 0
XS Weighting Method= 0
Number of US Weighted Cross Sections= 1
Number of DS Weighted Cross Sections= 1
Upstream XS Weight=0
Main XS Weight=1
Downstream XS Weight=0
Number of DS XS's Weighted with US Boundary= 1
Upstream Boundary Weight= 1
Weight of XSs Associated with US Boundary= 0
Number of US XS's Weighted with DS Boundary= 1
Downstream Boundary Weight= 0.5
Weight of XSs Associated with DS Boundary= 0.5
Percentile Method= 0
Sediment Output Level= 3
Mass or Volume Output= 0
Output Increment Type= 1
Profile and TS Output Increment= 1
Transport Output Increment 1
XS Output Flag= 0
XS Output Increment= 10
Read HDF5 Sediment Hotstart= 0
Sediment Hotstart Type= 0
Write Gradation File= 0
Read Gradation Hotstart= 0
Write HDF5 File= 1
Write Binary Output= 1
Write DSS Sediment File= 0
DSS Sediment Output Type= 1
SV Curve= 0
Specific Gage Flag= 0
Subcell Erosion Methods= 0
Subcell Deposition Methods= 0
Advection Scheme= 1
Matrix Solver= 0
Implicit Weighting Factor= 1
Maximum Outer Loop Convergence Iterations= 5
Convergence Maximum Absolute= 0.001
Convergence RMSE= 0.0001
Grain Fractions Max Abs Error= 0.001
Max Subgrid Regions= 1
Max Subgrid Length Scale= 3.402823E+38
Initial Layer Thickness= 3.402823E+38
Min Layer Thickness= 3.402823E+38
Max Layer Thickness= 3.402823E+38
Number of Layers= 5

--- LFFILESCK.f01 (steady flow) ---

Flow Title=Flow
Program Version=6.20
Number of Profiles= 1
Profile Names=P100yr
River Rch & RM=LFFILESCK,Main,16036
     857
River Rch & RM=LFFILESCK,Main,11876
    1030
River Rch & RM=LFFILESCK,Main,10757
    1210
River Rch & RM=LFFILESCK,Main,5047
    1360
Boundary for River Rch & Prof#=LFFILESCK,Main            , 1
Up Type= 0
Dn Type= 3
Dn Slope=0.01497
DSS Import GetInterval= 0
DSS Import GetPeak= 0
DSS Import FillOption= 0

--- LFFILESCK.g01 (geometry) ---

Geom Title=Geometry
Program Version=6.20

River Reach=LFFILESCK       ,Main
Reach XY= 30
2311737.00972155670318.6368971772311957.76500002670120.881000012
2311917.07400002669645.2820000052311278.48700002669131.428000003
2311086.95500003668017.0970000182310457.74400003667731.288000017
2310094.57800002667414.0509999992309847.24400002667504.371000022
2309504.45100002667409.863000005      2309148.22667452.983999997
2308965.90300001667622.9960000072308169.34200002667638.472000018
2307281.99900001666936.5120000092306481.67299999666578.381999999
2306310.88200001666284.0390000052305777.38899998666276.695999995
2305627.94600002666373.324000016     2304705.839666058.334000021
2304353.31000005665773.2410000262303613.32700005665867.831000015
2303192.20899999 665643.23800002     2302657.149665502.250000015
2302410.65000001665575.5080000012302217.91400003665762.510000005
2301597.15185347665593.0757327042301344.50699998665655.881000012
2301091.17700005665564.1660000092300386.34608085665558.558434159
2299808.88200001665342.8320000022299452.53093168665072.852208212

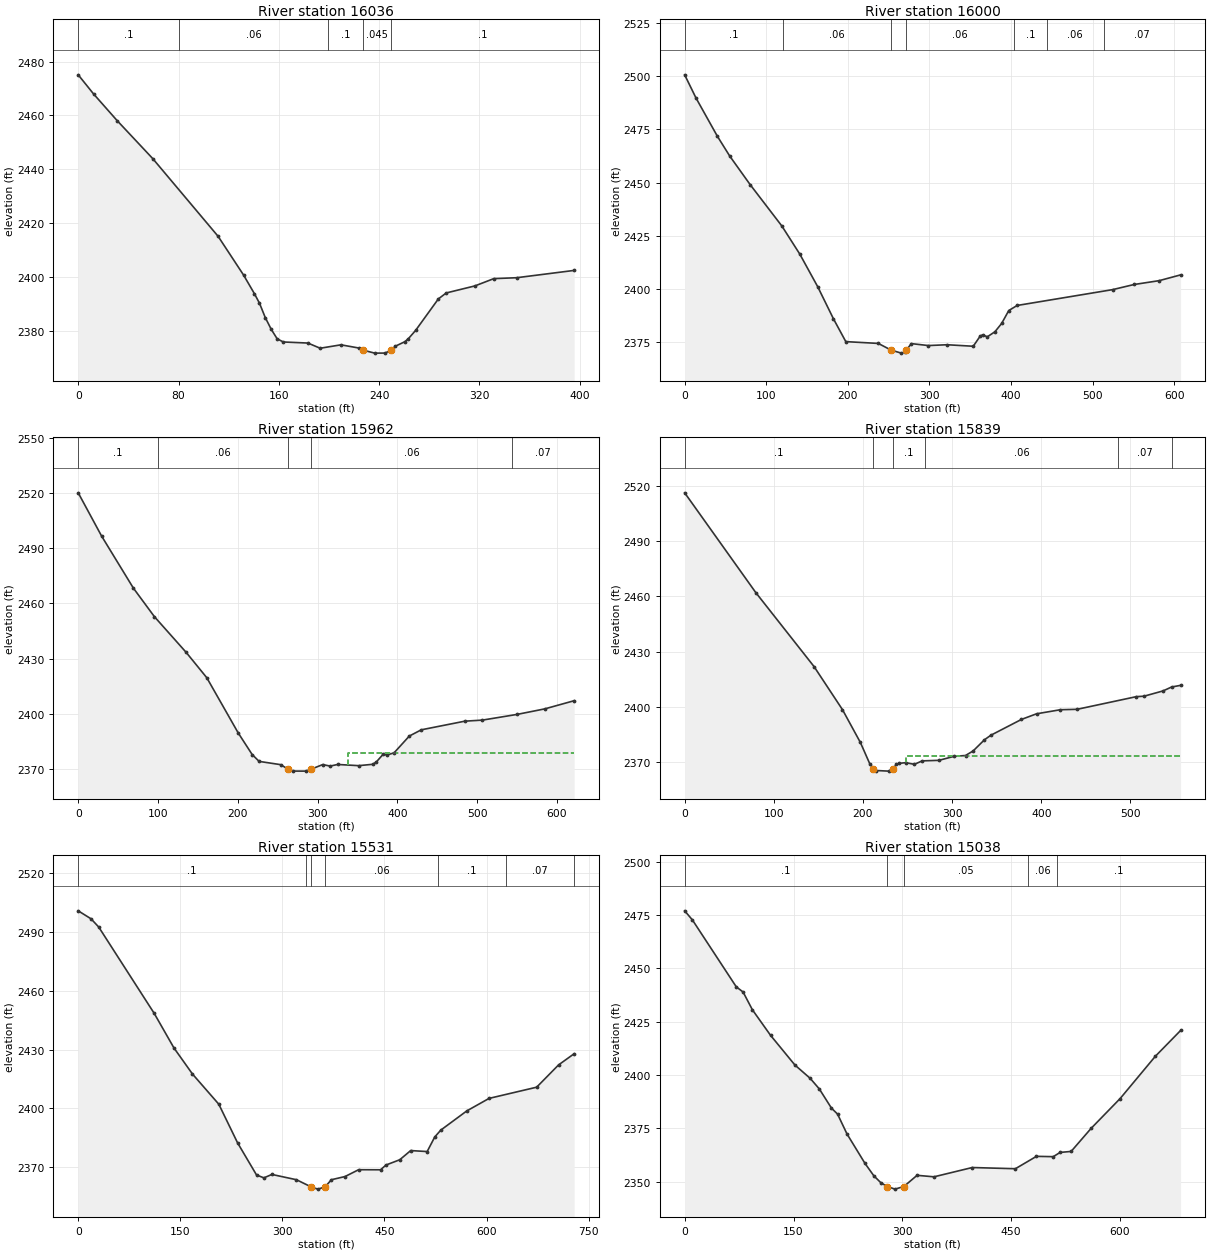
Type RM Length L Ch R = 1 ,16036   ,31.9,35.3,38.6
XS GIS Cut Line= 5
 2311926.4929505670456.701425856 2311791.5228368670371.698584684
 2311741.3543004670336.2759348182311732.27389828670299.409402902
2311627.36462561670211.749385274
#Sta/Elev= 30
       0 2475.12    12.2 2468.04    31.1 2458.06    59.5 2443.93   111.6 2415.04
   131.9 2400.64   140.6 2393.66   144.6 2390.16   149.2 2384.83     154 2380.42
   158.7 2376.92   163.6 2375.74   183.2 2375.34     193 2373.41   209.6 2374.68
   224.1 2373.47  227.352372.684   236.5 2371.59   244.7 2371.61  249.742372.685
   252.9 2374.15   260.5 2375.83   263.4 2376.98   269.1 2380.02   287.3 2391.77
   293.6 2393.98   316.4 2396.59   331.5  2399.3   349.7 2399.64   395.6 2402.36
#Mann= 5, -1 ,  0
       0     0.1       0      80    0.06       0  199.51     0.1       0
  227.35   0.045       0  249.74     0.1       0
Bank Sta=227.35,249.74
XS Rating Curve= 0 ,0
Exp/Cntr=0.3,0.1

Type RM Length L Ch R = 1 ,16000   ,40.5,38.8,48.4
XS GIS Cut Line= 6
2311976.87859864670433.483880595 2311765.8171805670339.327601147
2311774.15076119670289.0572918362311785.72302802670252.565364664
 2311803.9277785670224.6772362572311572.17756772670120.070724811
#Sta/Elev= 30
       0 2500.63    13.9 2489.72    40.1 2471.74    55.2 2462.46    80.2 2449.05
   119.1 2429.58     141 2416.43     163 2401.08   182.4 2385.92   197.5 2375.23
   237.3 2374.38  253.27  2371.2   265.6 2369.82   269.7 2370.28  271.48  2371.2
   277.9 2374.29   298.7 2373.38   321.7 2373.76   353.7 2373.05   362.2 2377.81
   365.2 2378.41     371  2377.5   380.3 2379.87   388.5 2383.76   397.3 2389.85
   407.5 2392.22   524.6 2399.67   550.9 2402.08   581.6 2403.88   607.9  2406.6
#Mann= 7, -1 ,  0
       0     0.1       0     120    0.06       0  253.27   0.045       0
  271.48    0.06       0  403.67     0.1       0  443.67    0.06       0
  513.67    0.07       0
Bank Sta=253.27,271.48
XS Rating Curve= 0 ,0
Exp/Cntr(USF)=0,0
Exp/Cntr=0.3,0.1

Type RM Length L Ch R = 1 ,15962   ,130.1,122.6,100.7
XS GIS Cut Line= 6
2312011.30191003670424.9377105682311800.24049189 670330.78143112
2311805.61699556670294.758856533 2311814.7570518670259.273932314
2311834.98466158670225.1056000192311584.53986044670105.319893282
#Sta/Elev= 30
       0 2520.16    29.4 2496.59    69.2 2468.33    95.5 2452.85   135.4  2433.4
   161.2 2419.64   200.6 2389.62   218.1 2377.88   226.8 2374.17   253.6 2372.41
  263.462369.893   269.1 2368.91   285.6 2368.88  291.682369.892   306.5 2372.44
   315.8 2371.63   325.3  2372.5   351.6 2371.85   369.3  2372.6   373.8 2373.91
   382.1 2377.97   387.1 2377.67   395.9  2378.8   415.1 2387.96   430.1 2391.34
   484.6 2396.03   506.8 2396.62   550.1 2399.71   584.9 2402.72   621.7 2407.16
#Mann= 5, -1 ,  0
       0     0.1       0     100    0.06       0  263.46   0.045       0
  291.68    0.06       0  544.05    0.07       0
#XS Ineff= 2 , 0
                          338.42          2378.7
Permanent Ineff=
       F       F
Bank Sta=263.46,291.68
XS Rating Curve= 0 ,0
Exp/Cntr(USF)=0,0
Exp/Cntr=0.3,0.1

Type RM Length L Ch R = 1 ,15839   ,313,308.5,300.5
XS GIS Cut Line= 3
2312082.63298125670336.0407013222311852.36401744670182.979566558
2311589.58649404670086.808411087
#Sta/Elev= 30
       0 2516.27    79.8 2462.01   145.2 2421.75     177 2398.38   197.1 2380.53
   207.5 2369.09  211.63 2366.31   214.7  2365.3   228.7 2364.96   233.5 2366.32
   237.5 2368.57   240.4 2369.17   247.9 2369.56   257.7 2368.66   266.4 2370.53
   285.2 2370.83   302.3 2373.01     315 2373.45   323.6 2375.95   336.3 2382.02
   343.5 2384.49   377.8 2393.08   394.7 2396.13   421.5 2398.35   440.2 2398.57
   506.7 2405.46   515.2 2405.69   536.5 2408.56   546.2  2410.7   556.3  2411.6
#Mann= 6, -1 ,  0
       0     0.1       0  211.63   0.045       0   233.5     0.1       0
     270    0.06       0   486.5    0.07       0   546.5    0.06       0
#XS Ineff= 2 , 0
                          247.72         2373.01
Permanent Ineff=
       F       F
Bank Sta=211.63,233.5
XS Rating Curve= 0 ,0
Exp/Cntr(USF)=0,0
Exp/Cntr=0.3,0.1

Type RM Length L Ch R = 1 ,15531   ,503.1,492.3,480.7
XS GIS Cut Line= 4
2312209.71766943670130.2169964722312003.70138522669933.865544149
2311879.77710183669933.3255391482311561.39970019669968.445927891
#Sta/Elev= 30
       0 2500.88    18.8 2496.82    30.1 2492.62   111.7  2448.5   140.7 2430.85
   167.9 2417.54   206.6 2402.12   234.2 2382.38   262.1 2365.95   272.9 2364.51
   284.6 2366.25   320.7 2363.55  342.712359.822   352.1 2358.75  362.562359.823
   372.1 2363.55   392.1 2365.18   412.1 2368.67   444.3 2368.63   452.4 2371.08
   472.5 2373.75   488.6 2378.44   512.8 2377.94     524 2385.42   532.9 2388.91
   571.1 2398.71   603.8 2405.09   673.7 2410.81   705.9 2422.19   728.8  2427.9
#Mann= 7, -1 ,  0
       0     0.1       0   334.6    0.06       0  342.71   0.045       0
  362.56    0.06       0  528.52     0.1       0  628.52    0.07       0
  728.52     0.1       0
Bank Sta=342.71,362.56
XS Rating Curve= 0 ,0
Exp/Cntr=0.3,0.1

Type RM Length L Ch R = 1 ,15038   ,405.1,398.8,394.7
XS GIS Cut Line= 4
2312024.79833403669420.4043290142311776.54841554669500.106216838
2311699.23891093 669632.115128042311503.91779205669818.176980293
#Sta/Elev= 30
       0 2476.96    10.7 2472.67    71.1 2441.35    80.5 2438.92    93.3 2430.61
   118.3 2418.65   151.9 2404.72   172.9 2398.49   185.6 2393.49   202.3 2384.51
   210.7 2381.72   223.7 2372.41   248.5 2358.62   260.7  2352.8   270.6 2349.49
  279.392347.775   289.8 2346.56  302.022347.776   320.3 2353.03   343.6 2352.33
   396.3 2356.68   455.8 2356.12   484.8 2361.92     508 2361.77   517.4 2363.76
   532.6 2364.22   560.2 2375.05   600.2 2389.02   648.6 2408.78   683.5  2420.9
#Mann= 5, -1 ,  0
       0     0.1       0  279.39   0.045       0  302.02    0.05       0
  473.71    0.06       0  513.71     0.1       0
Bank Sta=279.39,302.02
XS Rating Curve= 0 ,0
Exp/Cntr=0.3,0.1

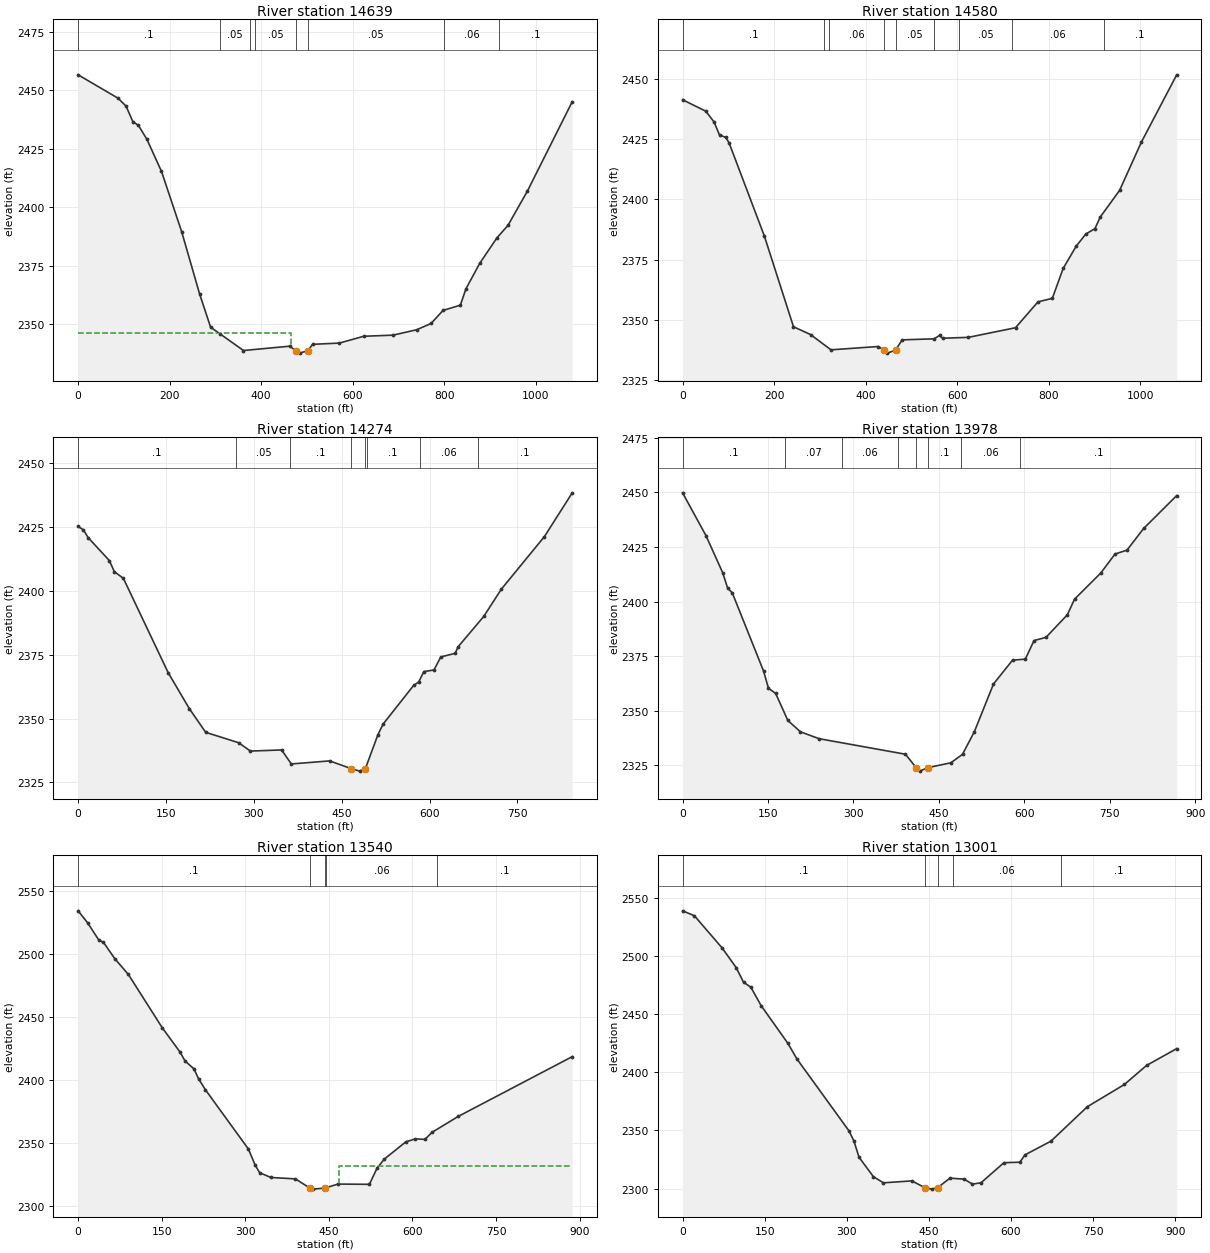
Type RM Length L Ch R = 1 ,14639   ,59.4,59.6,59.2
XS GIS Cut Line= 6
2311797.98712902668969.8837489342311462.73110483669141.213325967
2311485.99808443669197.2655949962311477.53736458669297.736643256
2311551.56866329669377.0558918822311321.01404729669739.809255598
#Sta/Elev= 30
       0 2456.67    87.4 2446.64   104.9 2443.22   119.7 2436.57   131.6 2435.07
   150.3 2429.06   182.2 2415.31   226.3 2389.48   265.4 2362.89   289.5  2348.6
     310 2345.74   361.4 2338.59   462.7 2340.45  475.712338.521   483.9 2337.47
   502.22338.527   512.4 2341.24   571.2 2341.78   624.1 2344.69   688.2 2345.17
   740.3  2347.5   771.5 2350.19   797.5 2355.76   835.4    2358   847.5 2364.99
   877.7 2375.92   915.7 2386.95   939.4 2392.17     982 2406.91  1079.9 2445.16
#Mann= 8, -1 ,  0
       0     0.1       0     310    0.05       0   376.5    0.06       0
   386.5    0.05       0  475.71   0.045       0   502.2    0.05       0
   800.1    0.06       0   920.1     0.1       0
#XS Ineff= 2 , 0
          465.33  2346.1
Permanent Ineff=
       F       F
Bank Sta=475.71,502.2
XS Rating Curve= 0 ,0
Exp/Cntr(USF)=0,0
Exp/Cntr=0.3,0.1

Type RM Length L Ch R = 1 ,14580   ,290.7,306.3,319.1
XS GIS Cut Line= 6
2311748.02742436668968.6347563182311412.77140017 669139.96433335
2311436.03837977669196.0166023792311427.57765991669296.487650639
2311501.60895863669375.8068992652311271.05434262669738.560262982
#Sta/Elev= 30
       0 2441.31    50.8 2436.55    68.7  2432.1    80.7 2426.68    94.2 2425.69
   101.4 2423.51   178.7 2384.77   242.4  2347.1   279.7 2343.87   324.3 2337.53
   427.7 2338.91   439.8 2337.45   447.8 2336.16  465.332337.434     480 2341.67
   549.8  2342.1   561.5 2343.51   568.1 2342.34   624.6 2342.71   727.6  2346.7
   776.7 2357.43   808.1 2358.91   831.7 2371.28   860.3 2380.56   881.1 2385.54
   901.3 2387.87   912.9 2392.67   955.1  2403.7  1002.4 2423.62  1079.9 2451.65
#Mann= 9, -1 ,  0
       0     0.1       0     310    0.05       0     320    0.06       0
   439.8   0.045       0  465.33    0.05       0  549.71    0.06       0
  604.55    0.05       0   720.1    0.06       0   920.1     0.1       0
Bank Sta=439.8,465.33
XS Rating Curve= 0 ,0
Exp/Cntr(USF)=0,0
Exp/Cntr=0.3,0.1

Type RM Length L Ch R = 1 ,14274   ,295.5,295.6,296.5
XS GIS Cut Line= 4
2311725.24415369668932.5133511162311403.92418964668959.568235488
2311231.25707863669011.9900364532310943.26318354669193.832448139
#Sta/Elev= 30
       0 2425.27     9.1 2423.91    17.1  2420.9    53.3 2411.89    61.8 2407.56
    77.3 2404.92   153.6 2368.02   189.7 2353.93   217.8 2344.59     274 2340.53
   294.1 2337.25   347.3 2337.69     364  2332.2   429.4  2333.4  466.332330.357
   480.7 2329.39  490.362330.358   511.8 2343.68   520.7 2347.85   572.7 2362.96
   581.4 2364.33   590.1 2368.37   607.5 2369.04   619.1 2374.13   643.7 2375.55
   648.5 2378.08   692.4 2389.99   722.4 2400.67     796 2421.29   843.5 2438.44
#Mann= 8, -1 ,  0
       0     0.1       0     270    0.05       0  362.46     0.1       0
  466.33   0.045       0  490.36    0.05       0  492.46     0.1       0
  582.91    0.06       0  682.91     0.1       0
Bank Sta=466.33,490.36
XS Rating Curve= 0 ,0
Exp/Cntr=0.3,0.1

Type RM Length L Ch R = 1 ,13978   ,432.5,438.3,441.9
XS GIS Cut Line= 4
2311626.96644917668589.6308023852311278.09022283668707.923723775
2311158.93562293668743.7929222022310800.69873651668853.903053945
#Sta/Elev= 30
       0 2449.76      41  2430.2    70.5 2413.14      79 2406.22    87.4 2403.86
   142.3 2368.07   150.8 2360.25   163.4 2357.92   184.8 2345.55   206.9 2340.34
   239.5 2337.19   391.3 2330.07  410.132323.934   416.3 2322.33   430.72323.936
     471 2326.14   491.5 2330.02   512.4 2340.43   545.9 2362.23   579.4 2373.15
   601.8 2373.62   617.1 2382.12     638 2383.57   675.7 2393.95   688.2 2401.07
   734.2 2413.02   759.3 2421.74   780.3 2423.52   809.6 2433.45   867.6  2448.5
#Mann= 8, -1 ,  0
       0     0.1       0     180    0.07       0     280    0.06       0
  378.39     0.1       0  410.13   0.045       0   430.7     0.1       0
  488.39    0.06       0  592.82     0.1       0
Bank Sta=410.13,430.7
XS Rating Curve= 0 ,0
Exp/Cntr=0.3,0.1

Type RM Length L Ch R = 1 ,13540   ,553.2,538.8,520.6
XS GIS Cut Line= 4
2311600.94257866668264.7001567172311270.76576319668323.505314164
 2311102.8996013668311.1326998572310745.43189572668449.294000605
#Sta/Elev= 30
       0 2534.62      17 2525.13    37.3 2511.32    45.5 2509.61    65.8 2496.66
    90.2 2484.12   151.1 2441.75   183.3 2422.31   191.7 2415.56     208 2409.13
   216.1 2401.39   228.3 2392.74   305.5 2345.65   317.7 2332.96   325.8 2326.77
     346    2323   390.1 2321.88  415.622314.675   422.1 2313.75  443.942314.674
   466.3 2317.77   522.8 2317.56   536.6 2330.42   549.5 2337.55   588.1 2351.22
   605.2 2353.63   622.4 2353.22   635.3 2358.82   682.4 2371.49   886.9  2418.9
#Mann= 5, -1 ,  0
       0     0.1       0  415.62   0.045       0  443.94     0.1       0
  445.37    0.06       0  643.69     0.1       0
#XS Ineff= 2 , 0
                          467.92         2331.98
Permanent Ineff=
       F       F
Bank Sta=415.62,443.94
XS Rating Curve= 0 ,0
Exp/Cntr=0.3,0.1

Type RM Length L Ch R = 1 ,13001   ,481.7,483.5,485.4
XS GIS Cut Line= 4
     2311089.984      667514.0292310933.24337354 667821.13632499
2310851.46400109668011.0299985752310661.14636923668306.273368562
#Sta/Elev= 30
       0 2538.64    21.5 2534.44    72.1 2506.84    97.8 2489.96   111.3 2477.35
   124.8 2472.98   143.4 2457.28   192.2 2424.97   208.8 2411.49     304 2349.63
   312.9 2341.14   322.4 2326.97   348.7 2310.26   366.9 2305.01   418.9 2306.67
   442.52300.875   455.2 2299.59     4662300.873   488.6 2309.03   514.7 2308.13
   529.5 2303.91   545.2 2305.03   587.1 2322.28   616.3 2322.72   625.5 2328.98
   673.1 2340.82   739.7 2370.43   807.2 2389.47   847.7 2405.83   902.8 2420.28
#Mann= 5, -1 ,  0
       0     0.1       0   442.5   0.045       0     466     0.1       0
  494.79    0.06       0  691.55     0.1       0
Bank Sta=442.5,466
XS Rating Curve= 0 ,0
Exp/Cntr=0.3,0.1

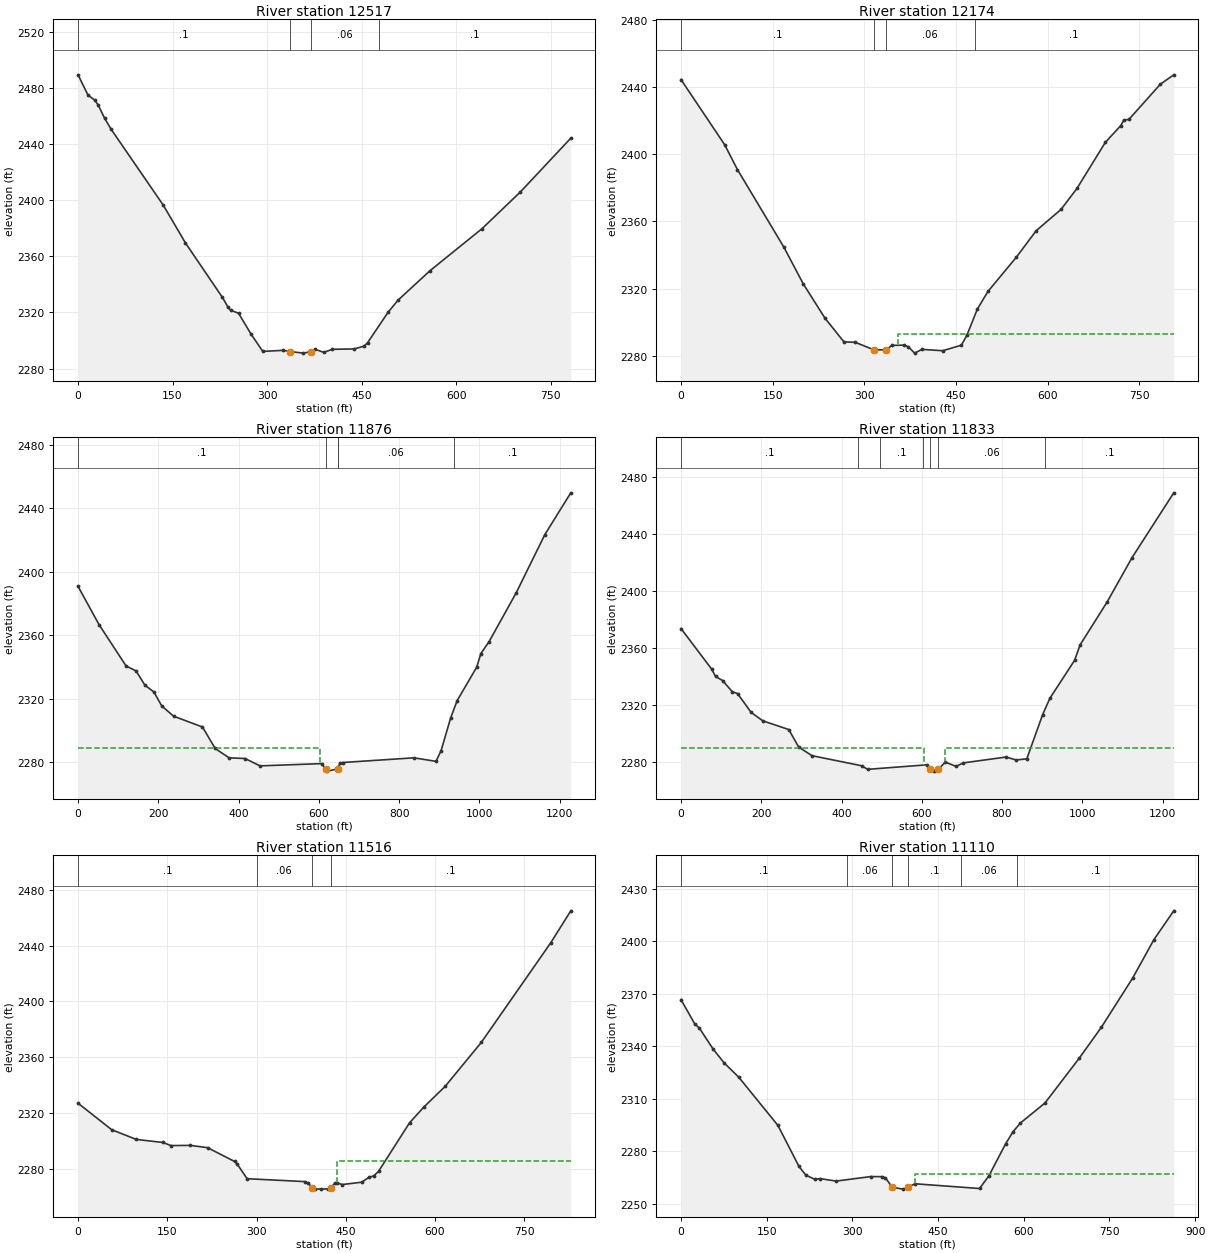
Type RM Length L Ch R = 1 ,12517   ,340.7,343.5,345.7
XS GIS Cut Line= 4
2310661.43067278667444.3469718672310480.49603543667669.277988233
2310402.05359352667806.7352579282310270.06740648      668114.738
#Sta/Elev= 30
       0 2489.16    15.7  2474.8    26.7 2471.08    31.9 2467.69    42.1 2458.29
    52.7 2450.26   135.2 2396.42   170.5 2369.45   229.1 2330.73   238.1 2323.66
   242.3 2321.53   254.7 2319.47   274.6 2304.56   293.2 2292.26   325.4 2293.05
  336.852292.162   357.6 2291.05     370 2292.17   376.8  2293.7   389.9  2291.6
   403.7 2293.77   438.4 2294.04   453.9 2296.01   459.4  2298.4   492.3 2320.31
   508.1 2328.87   558.4 2349.66   641.1 2379.64     702 2405.79     782 2444.07
#Mann= 4, -1 ,  0
       0     0.1       0  336.85   0.045       0     370    0.06       0
  476.94     0.1       0
Bank Sta=336.85,370
XS Rating Curve= 0 ,0
Exp/Cntr=0.3,0.1

Type RM Length L Ch R = 1 ,12174   ,320.2,297.9,282.3
XS GIS Cut Line= 4
2310468.64557289667357.2790475752310213.63839356667479.447480302
2310102.98941713667618.264398779     2309980.496      667941.622
#Sta/Elev= 30
       0 2444.49    71.5 2405.64    92.3 2390.89   168.2 2344.72   200.1 2322.76
   235.6 2302.34   266.6 2288.23     285    2288  315.632283.506  335.412283.502
   344.8 2286.14   364.7 2286.32   371.9 2285.36   382.2 2281.55   394.2 2283.78
   428.2 2282.98   458.7 2286.29   467.7 2292.19   484.8 2307.77   502.1 2318.27
   548.5 2338.62   581.1 2354.49   621.7 2367.13   647.8 2379.65   694.3 2407.13
   719.1 2416.92   724.3 2420.23   732.9 2420.79   784.2  2441.7   806.1  2447.3
#Mann= 4, -1 ,  0
       0     0.1       0  315.63   0.045       0  335.41    0.06       0
  480.28     0.1       0
#XS Ineff= 2 , 0
                          354.23         2292.93
Permanent Ineff=
       F       F
Bank Sta=315.63,335.41
XS Rating Curve= 0 ,0
Exp/Cntr=0.3,0.1

Type RM Length L Ch R = 1 ,11876   ,40.3,42.9,42.7
XS GIS Cut Line= 6
2310059.90033273666952.0483212452309793.08624308667323.841354009
2309921.06943712667418.6722748972309975.03825389667462.618311406
2310096.08260006 667535.090722492309926.66079204667897.625762786
#Sta/Elev= 30
       0 2390.81    52.2 2366.79   119.8 2340.66   144.4  2337.6   166.8 2328.52
   188.8 2324.38   208.5 2315.54   238.1 2309.06   310.1 2302.24   341.7 2288.72
   376.2 2282.83   416.1 2282.39   453.5 2277.76   606.7 2279.17  616.962275.827
     621 2274.44  646.792275.825   652.6 2279.49     659 2279.86     837 2282.82
   891.9 2280.61   904.5 2287.21   928.5 2307.94   944.8 2318.91   993.4 2339.91
  1003.8  2348.5  1024.3 2356.04  1092.1 2386.91  1163.2 2423.46  1227.9 2449.78
#Mann= 5, -1 ,  0
       0     0.1       0  616.96   0.045       0  646.79     0.1       0
  647.01    0.06       0  937.74     0.1       0
#XS Ineff= 2 , 0
          602.64 2289.32
Permanent Ineff=
       F       F
Bank Sta=616.96,646.79
XS Rating Curve= 0 ,0
Exp/Cntr(USF)=0,0
Exp/Cntr=0.3,0.1

Type RM Length L Ch R = 1 ,11833   ,307,317.3,326
XS GIS Cut Line= 6
2310031.06733818 666979.363789772309764.25324852667351.156822534
2309892.23644257667445.9877434212309946.20525933 667489.93377993
2310067.24960551667562.4061910152309897.82779749667924.941231311
#Sta/Elev= 30
       0 2373.34    76.2 2344.95    86.1  2339.7   103.7 2336.84     128 2328.93
   140.9 2327.72   174.9 2314.47   203.9 2308.57   268.6 2302.46   293.2 2290.22
   326.3 2284.13   450.9 2277.01   464.8 2274.53     612  2277.7  620.532274.682
   630.6 2273.28  640.942274.654     659 2279.58   685.4  2276.6   703.2 2279.05
     810 2283.16   835.2 2281.12   861.7  2281.9   901.3 2312.99   919.1 2324.33
   980.9 2351.07   994.6 2361.88  1061.8 2391.95    1124 2423.12  1227.9 2468.58
#Mann= 7, -1 ,  0
       0     0.1       0     440    0.06       0  495.93     0.1       0
  604.09    0.06       0  620.53   0.045       0  640.94    0.06       0
  907.74     0.1       0
#XS Ineff= 2 , 0
          605.01 2289.57  656.92         2289.39
Permanent Ineff=
       F       F
Bank Sta=620.53,640.94
XS Rating Curve= 0 ,0
Exp/Cntr(USF)=0,0
Exp/Cntr=0.3,0.1

Type RM Length L Ch R = 1 ,11516   ,411.2,405.8,400.4
XS GIS Cut Line= 4
2309536.42203941667054.4622218832309630.93987075 667419.06291578
2309610.88079035667516.1685788642309645.42478084667866.858494393
#Sta/Elev= 30
       0 2327.15    56.5 2308.17    97.8 2301.23   142.5 2299.02   156.3  2296.8
   188.8 2296.94   217.7  2295.3   263.1 2285.41   267.3 2283.66   284.2 2273.07
     381 2271.01     387 2269.96  393.282266.769   397.7 2265.75   407.9 2265.61
   419.7 2265.75  424.712266.771   431.6 2269.73   434.9 2270.14   444.2 2268.89
   476.8 2270.58   488.9 2274.06   496.9 2275.09     505 2278.28   557.2 2313.14
   581.3 2324.43     617  2339.2   677.8 2370.71   794.4 2441.99   828.2 2464.94
#Mann= 4, -1 ,  0
       0     0.1       0     300    0.06       0  393.28   0.045       0
  424.71     0.1       0
#XS Ineff= 2 , 0
                          434.75         2285.89
Permanent Ineff=
       F       F
Bank Sta=393.28,424.71
XS Rating Curve= 0 ,0
Exp/Cntr=0.3,0.1

Type RM Length L Ch R = 1 ,11110   ,353.6,352.8,354.6
XS GIS Cut Line= 3
2309165.12539565667057.3631300972309253.38308774 667598.05762269
2309366.72454495667891.630577432
#Sta/Elev= 30
       0 2366.53    24.1 2352.67    32.2 2350.26    56.6 2338.12    75.7 2330.33
   101.1 2322.23   169.7 2294.65   206.5 2271.23   218.7 2266.19   234.9 2263.83
     243 2264.29   271.4 2262.86   332.2 2265.43   352.4 2265.39   357.9 2264.71
  369.62 2259.35   388.4 2258.26   398.1 2259.35   409.2 2261.33   522.6 2258.62
   538.9 2265.85   568.3 2284.22   581.2 2291.06   594.1 2296.04     637 2307.45
     697 2333.04   735.6 2350.65   790.6 2378.87   827.7 2400.79   862.5  2417.3
#Mann= 6, -1 ,  0
       0     0.1       0     290    0.06       0  369.62   0.045       0
   398.1     0.1       0     490    0.06       0  587.85     0.1       0
#XS Ineff= 2 , 0
                          409.42         2266.69
Permanent Ineff=
       F       F
Bank Sta=369.62,398.1
XS Rating Curve= 0 ,0
Exp/Cntr(USF)=0,0
Exp/Cntr=0.3,0.1

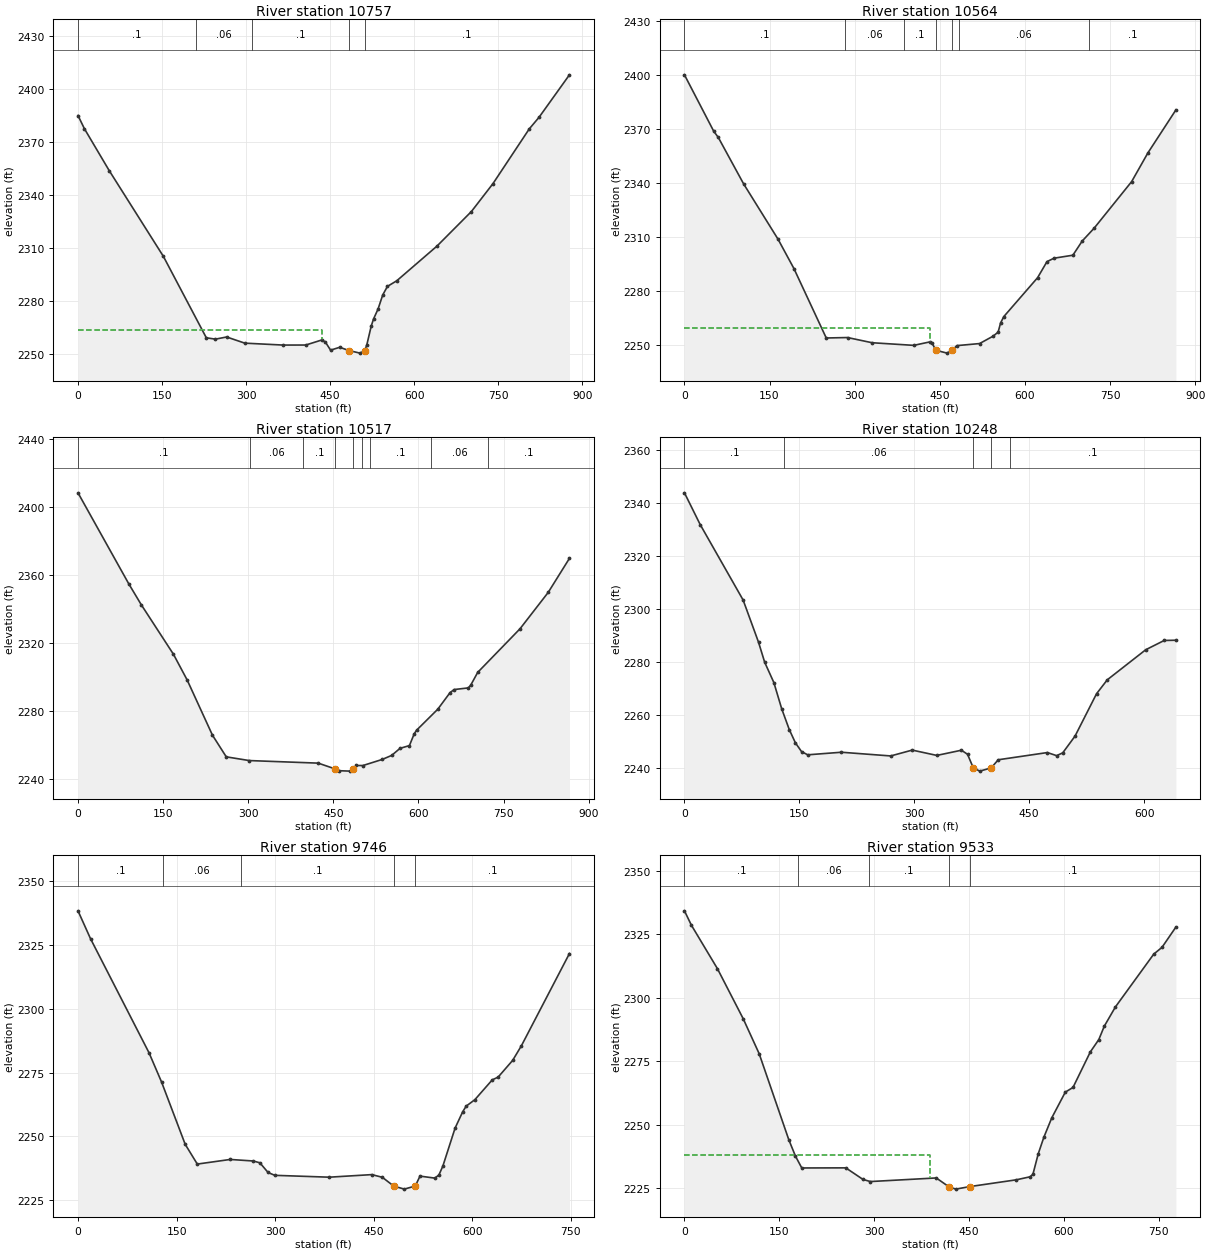
Type RM Length L Ch R = 1 ,10757   ,190.8,192.9,195.6
XS GIS Cut Line= 3
2308901.68578689667129.8874574542308969.25062224667658.368557655
2309064.92980596667989.301643017
#Sta/Elev= 30
       0  2384.8    11.4 2377.36    55.7 2353.64   152.5 2305.06   229.1 2259.02
   245.3 2258.26   265.4 2259.48   297.7    2256   366.2 2254.91   406.6 2254.93
   434.8 2257.75   441.4 2256.73   450.9 2252.03   467.1 2253.65   484.3 2251.77
   503.4 2250.35   511.9 2251.74   515.5 2254.93   523.5 2265.72   527.6 2269.68
   535.7 2275.35     544 2283.27   552.4 2288.12     569 2291.28   640.8 2310.91
   702.3 2330.48   740.9 2346.32   805.5  2377.2     823 2383.79   877.3 2407.82
#Mann= 5, -1 ,  0
       0     0.1       0     210    0.06       0     310     0.1       0
   484.3   0.045       0   511.9     0.1       0
#XS Ineff= 2 , 0
          435.81 2263.36
Permanent Ineff=
       F       F
Bank Sta=484.3,511.9
XS Rating Curve= 0 ,0
Exp/Cntr=0.3,0.1

Type RM Length L Ch R = 1 ,10564   ,46.9,47.4,49.1
XS GIS Cut Line= 6
2308714.80298688667154.2573980962308770.91893257667485.845879776
 2308775.0822413667555.2343584752308770.22504779  667639.1944177
2308723.04088227667678.051965771 2308804.7200404667980.562765315
#Sta/Elev= 30
       0    2400    51.5 2368.68    59.6  2365.2   104.2 2339.39   164.9  2308.6
   192.9 2292.28   249.9 2253.65   287.4  2253.9   330.7 2251.01   404.1 2249.55
   432.1 2251.45   436.1 2250.97  443.012246.824   462.9 2245.23  471.272246.822
   480.3 2249.41   520.1 2250.55   543.9 2254.66   552.8 2256.91   557.1 2261.99
   562.8 2265.55   622.3 2287.17   638.9 2296.12   651.3 2298.03   684.5 2299.68
     701 2307.58   721.8 2314.65   788.1 2340.63   816.7 2356.57   866.1 2380.51
#Mann= 7, -1 ,  0
       0     0.1       0   283.8    0.06       0  386.99     0.1       0
  443.01   0.045       0  471.27     0.1       0  483.49    0.06       0
  712.79     0.1       0
#XS Ineff= 2 , 0
          431.97 2258.97
Permanent Ineff=
       F       F
Bank Sta=443.01,471.27
XS Rating Curve= 0 ,0
Exp/Cntr=0.3,0.1

Type RM Length L Ch R = 1 ,10517   ,269.1,269.4,267.3
XS GIS Cut Line= 6
2308667.96576376667143.0164645472308724.08170945667474.604946227
2308728.24501817667543.9934249262308723.38782467667627.953484151
2308676.20365915667666.8110322222308757.88281727667969.321831766
#Sta/Elev= 30
       0 2408.16    89.6  2354.7   111.5 2342.51   168.2 2313.46   192.5 2298.28
     237 2265.95   261.3 2253.25   301.8 2251.07   423.4 2249.56   453.72246.098
   459.3 2245.13   479.6 2244.87  483.952246.099   490.5 2248.18   502.1 2248.15
   536.2 2251.73   552.8  2254.1   567.5 2258.23   584.1 2259.86   592.5 2266.76
   596.7 2268.88     634 2281.18   655.8 2290.99     663 2292.74   687.8  2293.7
     692 2295.24   704.4  2302.8     779  2328.4   828.7 2349.75   866.1 2369.72
#Mann= 9, -1 ,  0
       0     0.1       0   303.8    0.06       0  396.99     0.1       0
   453.7   0.045       0  483.95     0.1       0  500.52    0.06       0
  514.81     0.1       0  622.79    0.06       0  722.79     0.1       0
Bank Sta=453.7,483.95
XS Rating Curve= 0 ,0
Exp/Cntr=0.3,0.1

Type RM Length L Ch R = 1 ,10248   ,478.9,501.2,509
XS GIS Cut Line= 4
2308487.67524027667212.7703356452308461.43887413667556.498063768
2308450.48127251667708.6684362632308438.95253242 667852.46412932
#Sta/Elev= 30
       0 2343.95    20.5 2331.99    76.6 2303.47    96.7 2287.55   104.7 2280.01
   116.7 2272.33   126.9 2262.47   136.8  2254.6   144.8 2249.59   152.9 2246.24
   160.9 2245.06   204.9 2246.03   269.2 2244.63   297.3 2246.84   329.4 2244.83
   361.5 2246.79   369.5 2245.26  376.98 2240.15   385.5  2238.9   400.3 2240.12
   409.6 2243.19   473.7 2245.91   485.8 2244.74   493.8 2245.81   509.8 2252.11
   537.9 2268.11   551.9 2273.37   602.1 2284.72   626.2 2288.22   641.5 2288.31
#Mann= 5, -1 ,  0
       0     0.1       0     130    0.06       0  376.98   0.045       0
   400.3    0.06       0  424.73     0.1       0
Bank Sta=376.98,400.3
XS Rating Curve= 0 ,0
Exp/Cntr=0.3,0.1

Type RM Length L Ch R = 1 ,9746    ,225.9,212.9,206.5
XS GIS Cut Line= 5
2308289.26000888 667128.471559892308207.05136833 667286.44110448
2308044.24602135667502.4402776942307965.26124906667554.022169805
2307878.21680612667739.394594579
#Sta/Elev= 30
       0 2338.38    19.1 2327.44   108.1 2282.72   127.1  2271.3   163.1 2246.86
   181.5 2239.11   231.6 2240.92   266.7 2240.32   276.7 2239.61   289.2 2235.81
   299.4  2234.7   382.2 2233.97     447 2234.98     463 2233.93  480.242230.513
   496.4 2229.29  513.182230.514   520.3 2234.39   542.9 2233.61   549.1 2234.84
   555.1 2238.32   573.7 2253.21   585.2 2259.57   590.6 2261.83   603.8 2264.35
   630.3 2272.13   639.2  2273.2   661.3 2279.76   674.5 2285.44   747.7 2321.65
#Mann= 5, -1 ,  0
       0     0.1       0     130    0.06       0  248.08     0.1       0
  480.24   0.045       0  513.18     0.1       0
Bank Sta=480.24,513.18
XS Rating Curve= 0 ,0
Exp/Cntr(USF)=0,0
Exp/Cntr=0.3,0.1

Type RM Length L Ch R = 1 ,9533    ,38.9,36.1,36.9
XS GIS Cut Line= 4
2308082.16027118667000.5891321392307949.79400066667165.225303028
2307813.76983651667480.7030564282307727.09059292667685.444238998
#Sta/Elev= 30
       0 2334.19      11 2328.52    52.1 2311.44    92.9 2291.72   118.1 2277.98
     165  2244.1   175.5 2237.65   185.5 2232.99   255.1 2233.03   282.4 2228.46
     294 2227.64   398.1 2229.06  417.652225.672     429 2224.66  451.552225.672
   524.8 2228.33   546.6 2229.52     551  2230.5   559.4 2238.55   568.3 2245.09
   580.8 2252.71   602.2 2262.83   614.4 2264.69   641.8 2278.68   655.2 2283.53
   663.9 2288.82   681.5 2296.39   742.1 2317.17   755.1 2319.82   777.1 2327.81
#Mann= 5, -1 ,  0
       0     0.1       0     180    0.06       0  291.25     0.1       0
  417.65   0.045       0  451.55     0.1       0
#XS Ineff= 2 , 0
          388.08 2238.03
Permanent Ineff=
       F       F
Bank Sta=417.65,451.55
XS Rating Curve= 0 ,0
Exp/Cntr=0.3,0.1