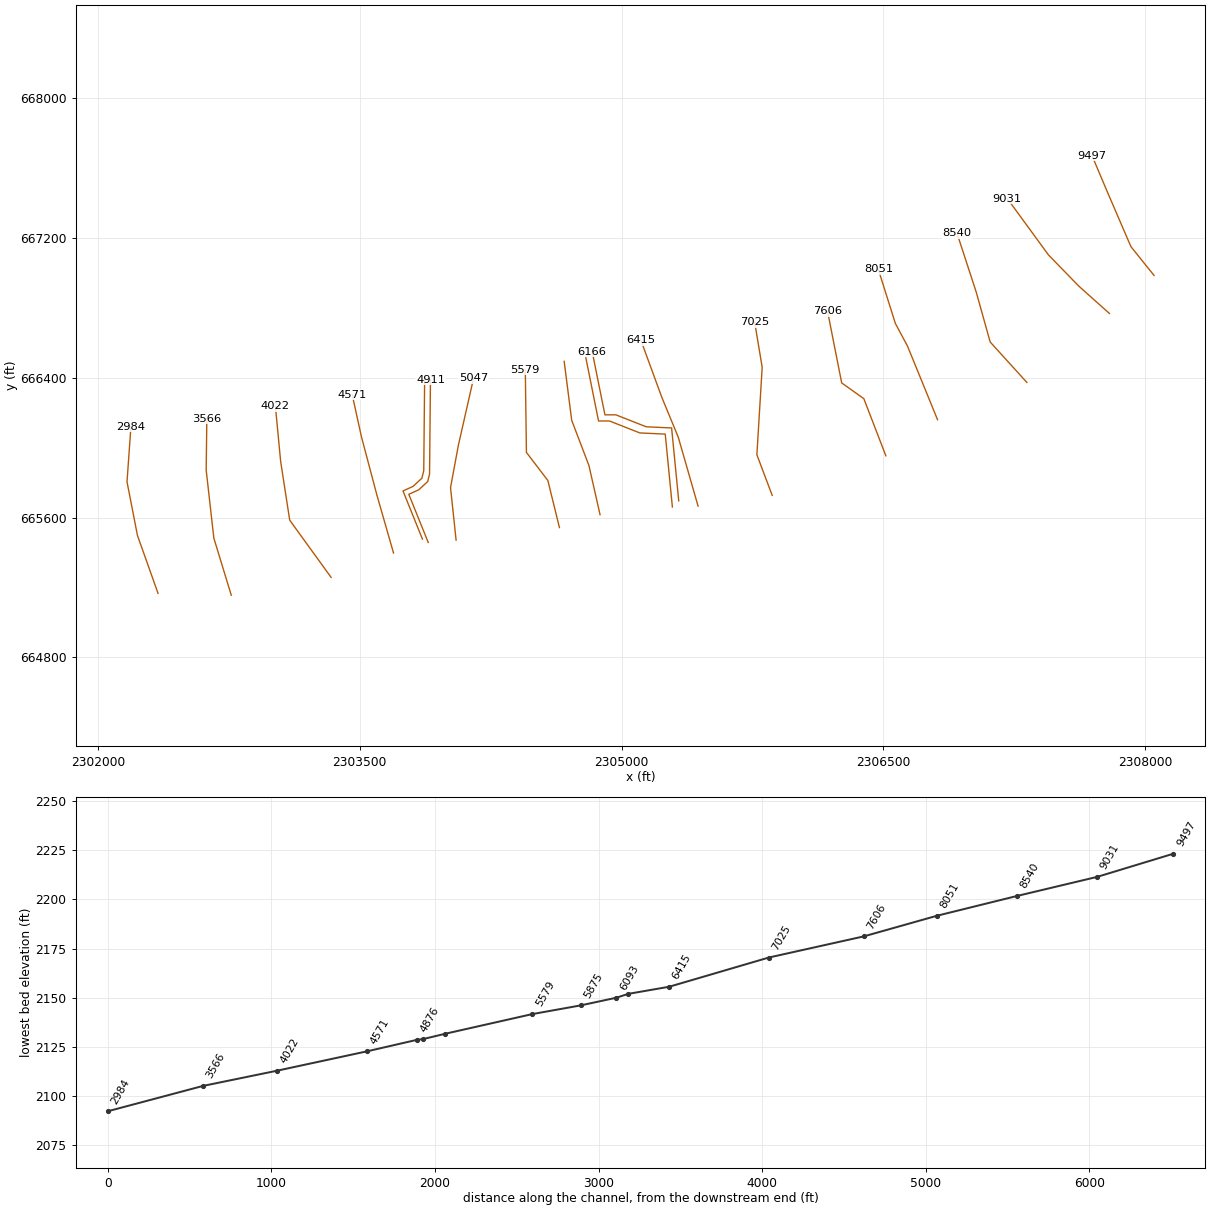
HEC-RAS study LFFILESCK.prj: LFFILESCK

--- LFFILESCK.g01 (geometry) --- (continued)

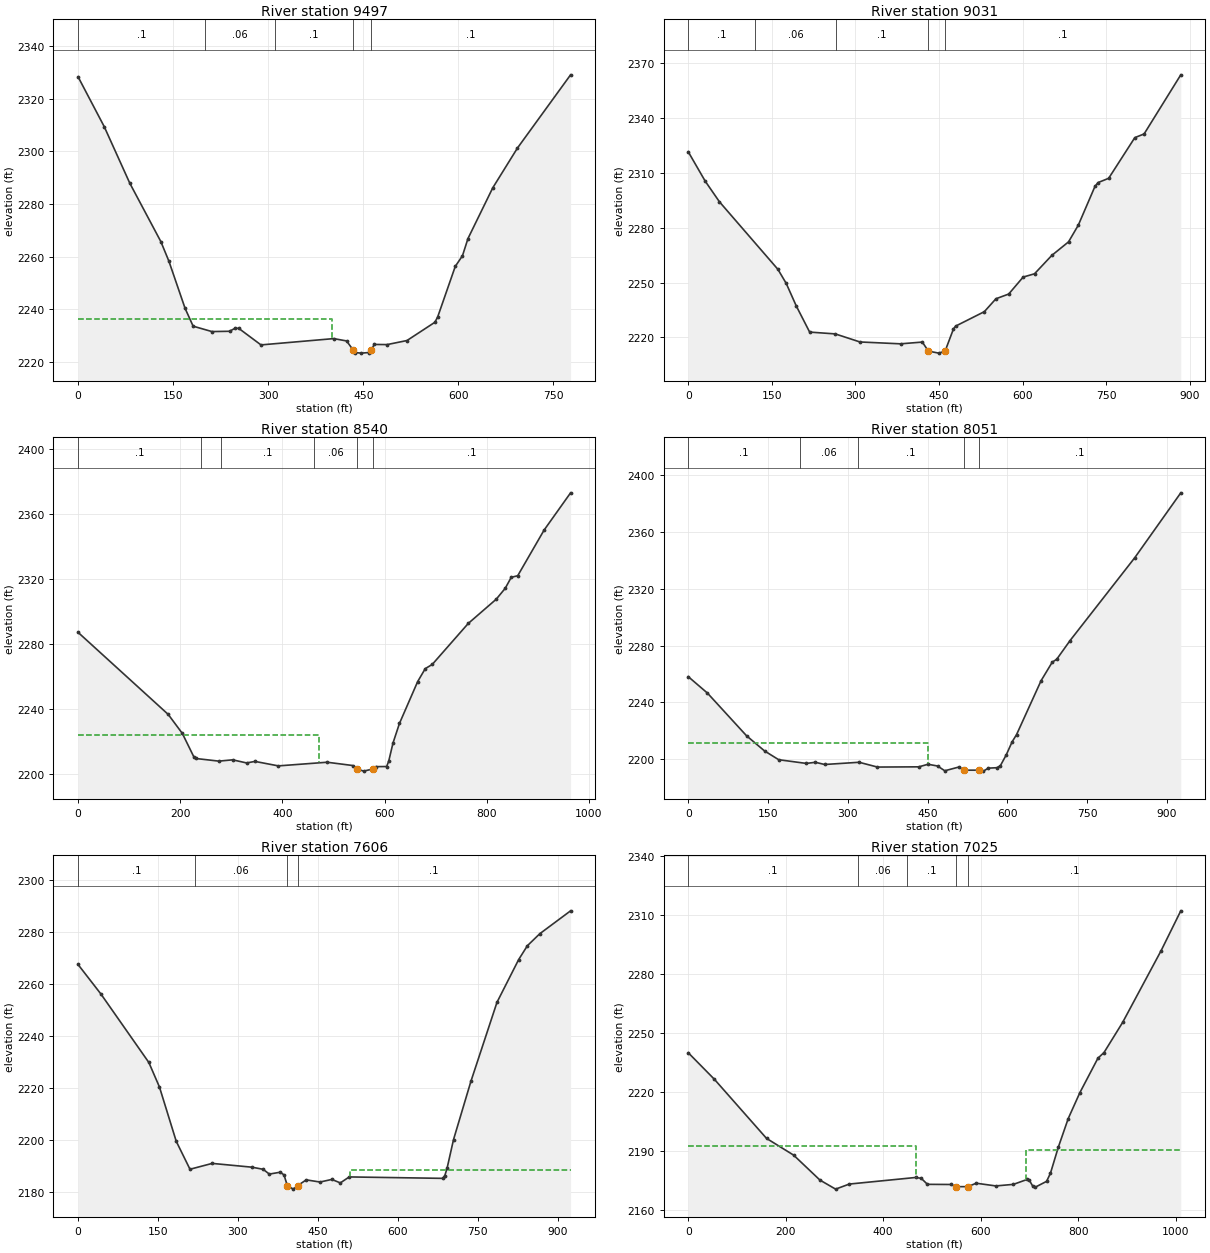
Type RM Length L Ch R = 1 ,9497    ,461.1,466.5,471.2
XS GIS Cut Line= 4
2308049.97734264 666985.484386262307917.61107212667150.120557149
2307781.58690797667465.5983105492307694.90766438667670.339493119
#Sta/Elev= 30
       0 2328.45    41.2 2309.51    81.7 2287.89   130.6  2265.7   143.3 2258.25
   168.9 2240.24   181.6 2233.46   211.2 2231.41     239 2231.52   248.1 2232.73
   253.8 2232.59   288.6 2226.33   403.4 2228.73   423.7 2227.84  434.062224.376
   436.7  2223.4   447.2  2223.2   458.5 2223.42  462.522224.378   467.4 2226.51
   487.6 2226.45     519    2228     563 2234.95   567.4 2236.97   595.2 2256.25
   606.5 2260.27   615.2 2266.84   654.3 2286.15   693.3 2301.32   777.1 2329.19
#Mann= 5, -1 ,  0
       0     0.1       0     200    0.06       0  311.25     0.1       0
  434.06   0.045       0  462.52     0.1       0
#XS Ineff= 2 , 0
          400.38  2236.3
Permanent Ineff=
       F       F
Bank Sta=434.06,462.52
XS Rating Curve= 0 ,0
Exp/Cntr=0.3,0.1

Type RM Length L Ch R = 1 ,9031    ,500.4,490.9,485.4
XS GIS Cut Line= 4
     2307794.062      666768.0862307618.92292492666924.475455646
2307445.09250031667103.0489995932307209.34264322667425.667674143
#Sta/Elev= 30
       0 2321.57    30.4 2305.52    55.9 2294.24   160.8 2257.28   175.8 2249.54
   193.8 2237.22   217.8 2222.92   263.7 2221.93     308 2217.52   380.9  2216.5
     420 2217.46  430.672212.525   449.4 2211.41   460.82212.522   475.8 2224.65
   479.6 2226.18   531.2  2234.1     552 2241.16   574.9 2243.74   600.8 2253.02
   621.2 2254.82   652.2 2264.88   682.2 2272.28   699.7 2281.39   729.6  2302.6
   735.2 2304.73   754.2 2307.06   801.1 2329.31   817.8 2331.34   883.6 2363.68
#Mann= 5, -1 ,  0
       0     0.1       0     120    0.06       0   264.8     0.1       0
  430.67   0.045       0   460.8     0.1       0
Bank Sta=430.67,460.8
XS Rating Curve= 0 ,0
Exp/Cntr=0.3,0.1

Type RM Length L Ch R = 1 ,8540    ,484.7,488.8,491.3
XS GIS Cut Line= 4
2307321.45784483666373.1798943122307111.32506215666604.551981167
2307031.60193413666889.5402214692306921.17731572667227.574946484
#Sta/Elev= 30
       0 2287.18   176.5 2236.62   204.2 2224.88   226.9 2210.32   230.3 2209.47
   275.6 2207.84   302.6 2208.64   329.8 2206.73   346.4 2207.66   392.1 2204.91
   487.6 2207.16   537.5 2205.14  546.482202.995     559 2201.68  577.082202.994
   583.2 2204.45     604 2204.51   608.1 2207.81   616.5    2219   629.1 2231.04
   664.8 2256.85   679.6  2264.8   693.4 2267.43   763.8 2292.66   818.5 2307.57
   836.1 2314.28     848 2321.08   860.6 2322.04   912.2 2350.15   964.1 2373.12
#Mann= 6, -1 ,  0
       0     0.1       0     240    0.06       0     280     0.1       0
  462.55    0.06       0  546.48   0.045       0  577.08     0.1       0
#XS Ineff= 2 , 0
           471.9 2223.94
Permanent Ineff=
       F       F
Bank Sta=546.48,577.08
XS Rating Curve= 0 ,0
Exp/Cntr=0.3,0.1

Type RM Length L Ch R = 1 ,8051    ,438.1,444.8,451.3
XS GIS Cut Line= 4
2306809.84868338 666159.746366772306637.57121718666581.640449382
2306568.45672371666710.1828715982306470.79163323667019.680701597
#Sta/Elev= 30
       0 2258.09    36.1 2246.53   109.6 2216.51   143.5 2205.83   170.1 2199.66
   221.9 2197.06   239.2 2197.84   256.5  2196.3   321.3 2197.86   355.8 2194.49
   433.6 2194.65   450.9 2196.46   468.8 2195.23   482.4 2191.88   509.3 2194.55
  518.062192.299     546 2192.29   555.1 2191.63   564.2 2193.73   580.5 2194.04
   586.9 2195.41   598.2 2203.23     609 2212.23   617.4 2217.34   663.5 2255.26
   684.5 2268.29   692.9 2270.33     718 2283.49   839.7 2341.79   926.2 2387.41
#Mann= 5, -1 ,  0
       0     0.1       0     210    0.06       0     320     0.1       0
  518.06   0.045       0     546     0.1       0
#XS Ineff= 2 , 0
          450.94 2211.17
Permanent Ineff=
       F       F
Bank Sta=518.06,546
XS Rating Curve= 0 ,0
Exp/Cntr=0.3,0.1

Type RM Length L Ch R = 1 ,7606    ,589.8,581,569.7
XS GIS Cut Line= 4
2306513.78784566665953.1844618162306387.55667828666280.389312221
2306260.77851221666370.3994533092306179.81697577 666780.69278083
#Sta/Elev= 30
       0 2267.54    42.9  2256.2   132.9 2229.87   152.8 2220.44   184.3 2199.57
   210.1 2188.83   251.8 2191.08   326.1 2189.63   347.3 2188.82     359 2186.97
   379.7  2187.7   386.6 2186.63  392.74 2182.55   403.9 2181.19412.30772182.561
   428.3 2184.75   454.1 2183.92   476.4 2184.92   492.2 2183.58     509 2185.88
   684.3 2185.33   688.4 2186.42   692.5 2189.12   704.7 2200.24   737.3 2222.61
   786.3 2253.02     827 2269.45   843.3 2274.75   866.6 2279.37   924.4 2288.17
#Mann= 4, -1 ,  0
       0     0.1       0     220    0.06       0  392.74   0.045       0
412.3077     0.1       0
#XS Ineff= 2 , 0
                          510.37         2188.59
Permanent Ineff=
       F       F
Bank Sta=392.74,412.3077
XS Rating Curve= 0 ,0
Exp/Cntr=0.3,0.1

Type RM Length L Ch R = 1 ,7025    ,602,609.9,613.2
XS GIS Cut Line= 4
2305862.72740163665726.9658090362305775.03769686665959.139434675
2305805.41621067666459.8919184542305762.63742983666716.876904518
#Sta/Elev= 30
       0 2239.86    53.7 2226.32   160.6 2196.25   216.2 2187.73   270.1 2175.04
   302.3 2170.42   330.4    2173   466.5 2176.35   477.9 2175.93   490.7 2172.86
   538.8 2172.78   549.7 2171.68   573.4 2171.68   590.8 2173.43   630.9 2172.05
     667 2172.84     695 2175.33     699 2175.23   707.1 2171.77   711.1 2171.31
   735.1 2174.38   743.1 2178.56     759 2191.64   779.5 2206.35   803.4 2219.55
   840.4 2237.07   852.9 2239.96     891 2255.25   970.1 2291.85  1010.4  2312.1
#Mann= 5, -1 ,  0
       0     0.1       0  348.18    0.06       0  448.18     0.1       0
   549.7   0.045       0   573.4     0.1       0
#XS Ineff= 2 , 0
          467.01  2192.2  692.88         2190.24
Permanent Ineff=
       F       F
Bank Sta=549.7,573.4
XS Rating Curve= 0 ,0
Exp/Cntr=0.3,0.1

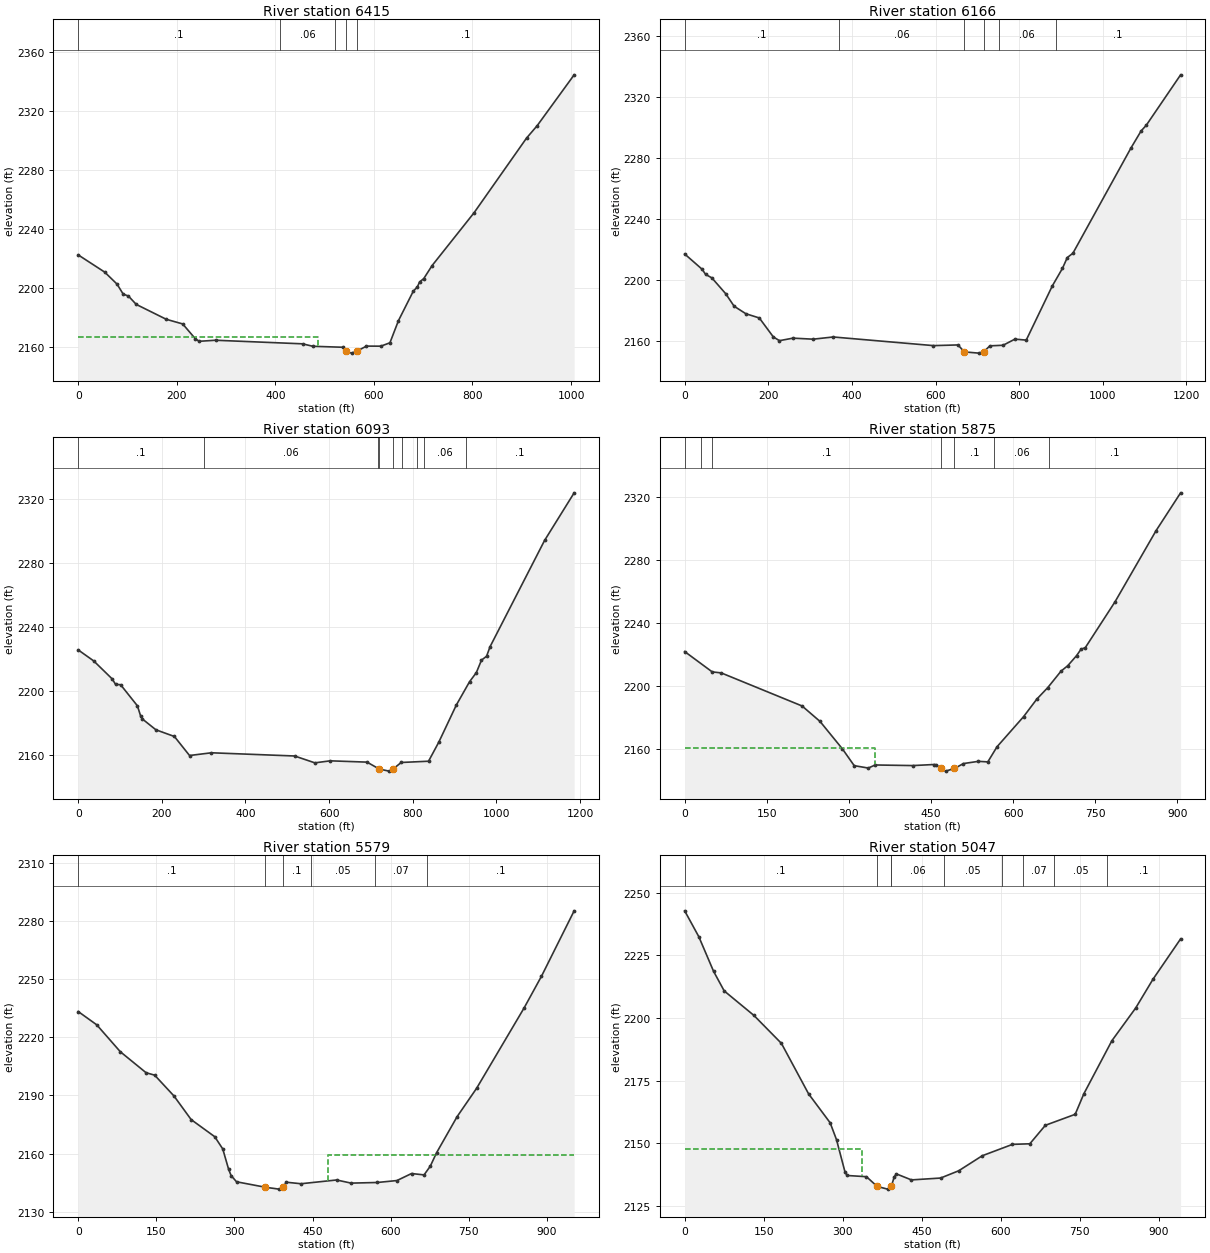
Type RM Length L Ch R = 1 ,6415    ,235.3,249.5,265.6
XS GIS Cut Line= 4
2305438.23170187665665.4439136842305324.71579744666059.920660454
2305230.10243832666289.2226534982305110.41849184666615.724494295
#Sta/Elev= 30
       0 2222.17    53.8 2210.49    78.8 2202.36    91.3 2195.57   101.8 2194.29
   117.8 2188.59   178.7  2178.5     212 2175.35   237.4  2165.4   245.3 2163.57
   278.6 2164.29   455.1 2161.86   476.2 2160.19   537.3 2159.53   543.1 2156.92
   554.6 2155.55   565.72156.924   584.9 2160.31     614 2160.27   632.5 2162.56
   649.8 2177.59   679.8  2197.5   688.3 2200.56   692.6 2203.81   701.1 2206.09
   718.1 2214.96   803.2 2250.77   909.8 2301.46   931.2  2309.8  1006.3 2344.33
#Mann= 5, -1 ,  0
       0     0.1       0     410    0.06       0  520.48     0.1       0
   543.1   0.045       0   565.7     0.1       0
#XS Ineff= 2 , 0
          487.14  2166.3
Permanent Ineff=
       F       F
Bank Sta=543.1,565.7
XS Rating Curve= 0 ,0
Exp/Cntr=0.3,0.1

Type RM Length L Ch R = 1 ,6166    ,81.1,72.9,73.3
XS GIS Cut Line= 6
2305327.48981728665695.5278955032305286.63425227666112.640726772
2305140.90268561666119.4819322752304967.39887628666187.770603586
2304904.67446708666187.7706035862304831.82767738666549.677038944
#Sta/Elev= 30
       0 2216.91    41.9 2206.85    49.9 2203.55      65 2201.25    98.1 2190.88
   118.2 2182.69   146.3 2177.75   178.5 2174.98     212 2162.55   226.7  2160.1
   258.9 2161.76   307.1 2161.08   355.3 2162.52     595 2156.86   653.5 2157.31
  668.972152.742   703.3 2151.94  714.79 2152.74   729.9 2156.72   761.4 2157.09
   789.7 2161.11   816.8 2160.47   879.3 2196.05   903.4 2207.48     915 2214.57
   928.4 2217.39  1067.2 2286.34  1091.6 2297.56  1103.9 2301.27    1186  2334.3
#Mann= 6, -1 ,  0
       0     0.1       0     370    0.06       0  668.97   0.045       0
  714.79     0.1       0  751.87    0.06       0  886.82     0.1       0
Bank Sta=668.97,714.79
XS Rating Curve= 0 ,0
Exp/Cntr(USF)=0,0
Exp/Cntr=0.3,0.1

Type RM Length L Ch R = 1 ,6093    ,224.5,217.6,201.7
XS GIS Cut Line= 6
 2305291.0236668665660.2909411062305250.16810179666077.403772375
2305104.43653513666084.244977878 2304930.9327258 666152.53364919
 2304868.2083166 666152.53364919 2304795.3615269666514.440084548
#Sta/Elev= 30
       0 2225.64    37.1 2218.77    81.3 2207.53    89.3 2204.14   101.4 2203.92
   141.6 2190.73   149.6 2184.12   153.6  2182.5   185.8 2175.78     230 2171.61
   266.2 2159.73   318.6 2161.43   517.5 2159.43   565.9 2155.15   602.8 2156.41
   690.7  2155.6   720.12151.264   743.4 2149.98  752.812151.264   772.4 2155.38
   837.8 2156.17   862.4 2168.12   904.4 2191.32   935.8 2205.77   952.1 2211.48
   964.4 2219.26   976.6  2221.7   984.8 2227.61  1115.3    2294    1186 2323.71
#Mann= 9, -1 ,  0
       0     0.1       0     300    0.06       0   717.4     0.1       0
   720.1   0.045       0  752.81     0.1       0  773.56    0.06       0
  809.71     0.1       0  826.82    0.06       0  926.82     0.1       0
Bank Sta=720.1,752.81
XS Rating Curve= 0 ,0
Exp/Cntr(USF)=0,0
Exp/Cntr=0.3,0.1

Type RM Length L Ch R = 1 ,5875    ,293.2,295.8,299.9
XS GIS Cut Line= 4
2304876.83806018 665616.091030092304813.23227328665897.233096063
2304714.41811412 666156.480682572304671.28029358666493.765634861
#Sta/Elev= 30
       0 2222.05    50.3 2209.12    66.7 2208.49   214.4 2187.47   247.2 2177.65
   288.2 2160.14   309.6 2149.55   335.3 2148.04   347.9 2149.99   416.6 2149.61
   455.1 2150.28   459.5 2150.09  467.55 2147.78   476.5 2146.08  492.742147.781
   509.1 2150.89   536.5  2152.3   553.6 2151.95   570.4 2161.55   618.8 2180.64
     643  2191.8   663.2 2199.19   687.4 2209.64   699.5 2213.02   715.6 2219.41
   723.7 2223.47   731.7 2224.56   785.9 2253.65   860.8 2298.82   905.7 2322.89
#Mann= 7, -1 ,  0
       0     0.1       0      30    0.06       0      50     0.1       0
  467.55   0.045       0  492.74     0.1       0  565.69    0.06       0
  665.69     0.1       0
#XS Ineff= 2 , 0
          346.91    2161
Permanent Ineff=
       F       F
Bank Sta=467.55,492.74
XS Rating Curve= 0 ,0
Exp/Cntr=0.3,0.1

Type RM Length L Ch R = 1 ,5579    ,549.6,532.3,523.6
XS GIS Cut Line= 4
2304644.13466071665542.5926724672304577.76575395665812.156329465
 2304455.0755108665972.6101154052304448.66654035666445.460863846
#Sta/Elev= 30
       0 2233.29    35.6 2226.43    80.9 2212.54   130.4 2201.71   146.8 2200.47
   183.9 2189.73   216.9 2177.54   262.2 2168.71   277.6 2162.39     289 2151.79
   293.7 2148.61   304.1 2145.45   359.4 2142.63   385.6 2141.66  393.162142.592
   399.7 2145.22   427.9 2144.44   496.2 2146.38   524.2 2144.76   574.6 2145.09
   612.2 2146.09   640.2 2149.71   664.2    2149   676.2  2153.5   688.2  2160.4
   727.7 2179.05   765.2  2193.7   856.2 2235.06   889.6 2251.42   952.5 2285.25
#Mann= 6, -1 ,  0
       0     0.1       0   359.4   0.045       0  393.16     0.1       0
  447.61    0.05       0   569.6    0.07       0   669.6     0.1       0
#XS Ineff= 2 , 0
                          478.87         2159.33
Permanent Ineff=
       F       F
Bank Sta=359.4,393.16
XS Rating Curve= 0 ,0
Exp/Cntr=0.3,0.1

Type RM Length L Ch R = 1 ,5047    ,135,136.5,138.8
XS GIS Cut Line= 4
2304052.23421218665470.5664219442304020.38139992665771.409601505
2304065.94064273666016.5298076592304152.14273719 666396.35094877
#Sta/Elev= 30
       0  2242.7    26.8 2232.39    54.9 2218.54      75 2210.75   131.3 2200.99
   183.6 2189.82   235.2 2169.67   276.1 2158.13   288.2 2151.37   304.3  2138.5
   308.4  2137.1     345 2136.62  365.242132.751     385 2131.66   392.1 2132.75
   397.9 2136.63     402 2137.72   430.4 2135.34   485.7 2136.08     520 2138.97
   564.8 2144.98   622.2 2149.52   655.1 2149.75   684.6 2157.13   741.2 2161.51
   757.6 2169.69   810.9 2190.89     856 2203.92   888.8 2215.39   941.3 2231.51
#Mann= 9, -1 ,  0
       0     0.1       0  365.24   0.045       0   392.1     0.1       0
  392.52    0.06       0  492.52    0.05       0  601.84    0.06       0
  641.84    0.07       0  701.84    0.05       0  801.84     0.1       0
#XS Ineff= 2 , 0
          336.78 2147.81
Permanent Ineff=
       F       F
Bank Sta=365.24,392.1
XS Rating Curve= 0 ,0
Exp/Cntr=0.3,0.1

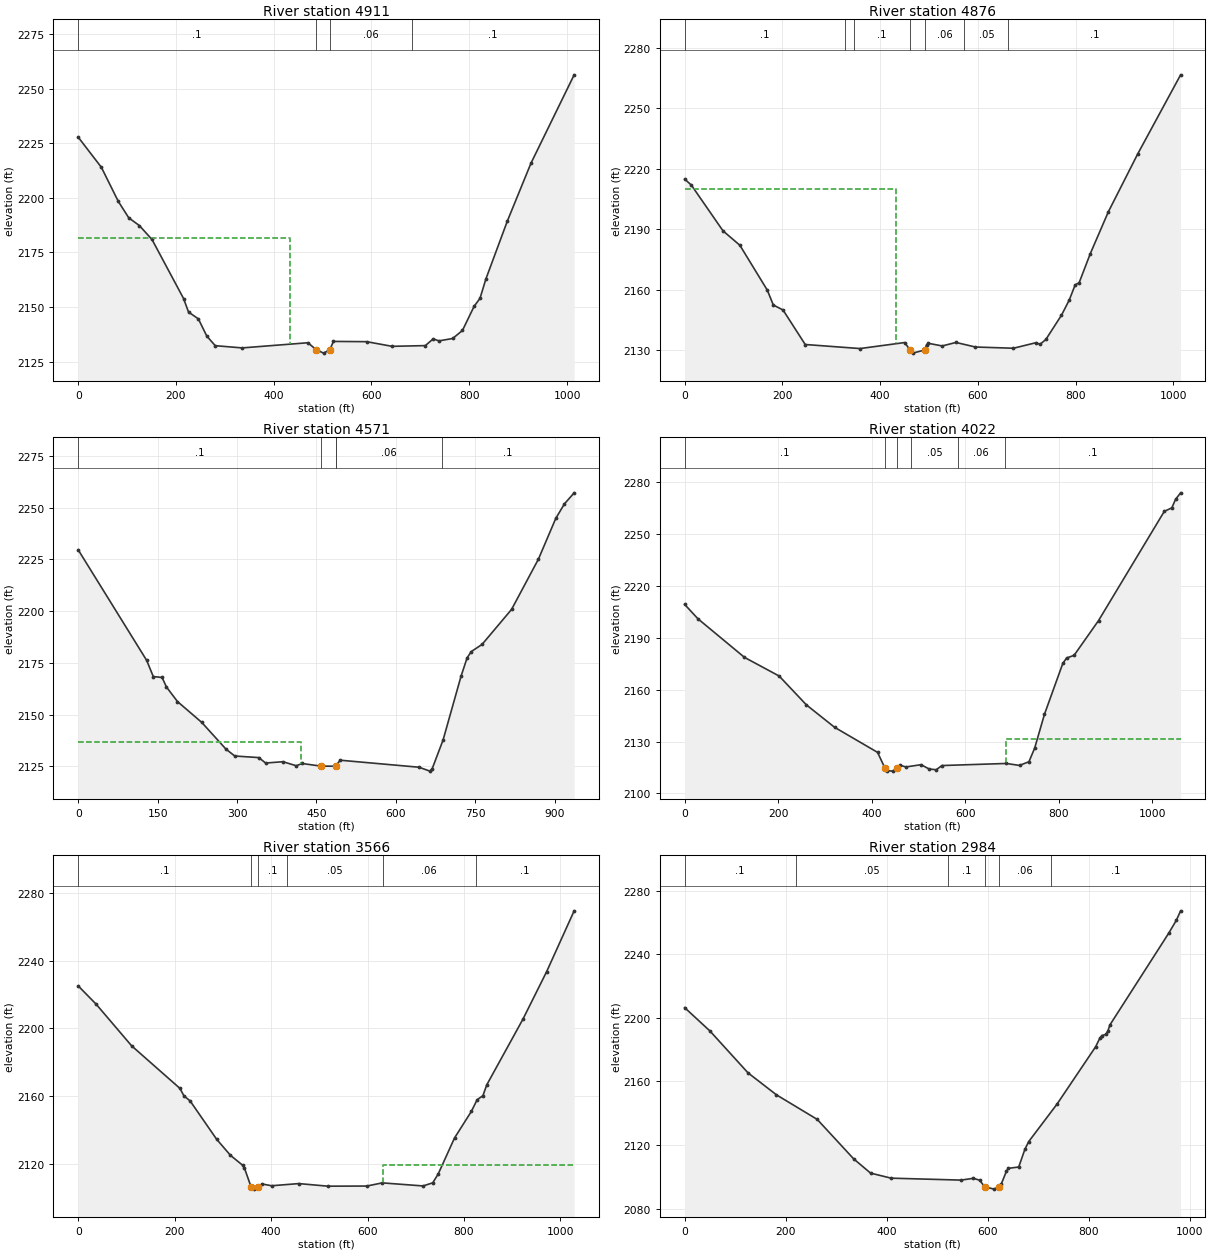
Type RM Length L Ch R = 1 ,4911    ,37.4,34.5,34.8
XS GIS Cut Line= 6
2303892.67137432665457.264434617 2303781.3933923665732.886265186
2303838.84272464665758.9995980682303889.76372376665806.003597254
2303900.20905691665849.0905965082303905.43172349666389.636587152
#Sta/Elev= 30
       0 2227.75    47.4 2213.95    81.9  2198.4   103.4 2190.84     125 2187.32
   150.9 2180.94   215.6 2153.88   225.7  2147.7   245.8 2144.61     263 2136.74
   280.3 2132.33   335.4 2131.31     470 2133.67  486.612130.524   502.1 2128.92
  514.932130.527   522.1 2134.28   590.1 2134.16   642.1 2132.03   710.1 2132.36
   726.1 2135.43   738.1 2134.53   766.1 2135.62   786.1 2139.31     810 2150.36
     822    2154   834.1  2162.9   878.1 2189.46   926.1 2215.75  1014.6 2256.28
#Mann= 4, -1 ,  0
       0     0.1       0  486.61   0.045       0  514.93    0.06       0
  682.39     0.1       0
#XS Ineff= 2 , 0
          432.79 2181.56
Permanent Ineff=
       F       F
Bank Sta=486.61,514.93
XS Rating Curve= 0 ,0
Exp/Cntr(USF)=0,0
Exp/Cntr=0.3,0.1

Type RM Length L Ch R = 1 ,4876    ,296.7,305,307.9
XS GIS Cut Line= 6
2303859.48308006665476.5218399272303748.20509804665752.143670496
2303805.65443038665778.257003378 2303856.5754295665825.261002564
2303867.02076265665868.3480018182303872.24342923666408.893992462
#Sta/Elev= 30
       0 2214.94    13.6 2211.97    78.4 2189.26   112.9 2182.11   169.1 2159.82
   181.3 2152.48   201.2 2150.01   246.6 2132.88   358.7 2130.87   450.1 2133.85
  461.122130.159   466.6  2128.6  491.112130.157   494.8 2132.66   498.8 2133.46
   526.9 2132.16   554.9  2133.9   594.9 2131.63   672.7 2131.03   718.9 2133.79
   726.9 2132.95   738.9 2135.37   770.9 2147.43   786.9 2155.01   798.9 2162.48
   806.9 2163.46   829.9 2178.01   866.9 2198.78   926.9 2227.45  1014.6 2266.66
#Mann= 7, -1 ,  0
       0     0.1       0  327.24    0.06       0  347.24     0.1       0
  461.12   0.045       0  491.11    0.06       0  572.39    0.05       0
  662.39     0.1       0
#XS Ineff= 2 , 0
          432.11 2210.05
Permanent Ineff=
       F       F
Bank Sta=461.12,491.11
XS Rating Curve= 0 ,0
Exp/Cntr(USF)=0,0
Exp/Cntr=0.3,0.1

Type RM Length L Ch R = 1 ,4571    ,547.3,549.5,545
XS GIS Cut Line= 4
2303693.86631505665396.9086842812303598.32799885665729.782335051
2303510.00747474666062.5412316822303457.24031908666303.021159876
#Sta/Elev= 30
       0  2229.6   129.3 2176.24   141.8 2168.44   158.4 2167.98   166.7 2163.38
   187.5 2156.36   233.3  2146.3   279.1 2133.38   295.7 2130.06   341.1  2129.3
     354 2126.67   386.8 2127.31   411.9 2125.35   422.8 2126.45   458.8 2125.16
  486.072125.156   494.8 2128.03   643.7 2124.64   664.4 2122.76   668.5 2123.83
   689.2 2137.79   723.1 2168.55   734.6 2177.46   742.4 2180.47   762.9 2183.96
   818.6 2200.85   869.4 2225.17   902.1  2244.8   918.5 2251.83   936.8 2257.14
#Mann= 5, -1 ,  0
       0     0.1       0   458.8   0.045       0  486.07     0.1       0
  486.31    0.06       0  686.31     0.1       0
#XS Ineff= 2 , 0
          420.06 2136.86
Permanent Ineff=
       F       F
Bank Sta=458.8,486.07
XS Rating Curve= 0 ,0
Exp/Cntr=0.3,0.1

Type RM Length L Ch R = 1 ,4022    ,454.9,455.4,455.4
XS GIS Cut Line= 4
2303336.23958108665257.5923170632303099.26606587665584.931185687
2303047.37397747665921.0806073782303017.39606587666235.903281105
#Sta/Elev= 30
       0 2209.26    28.4 2200.95   127.9 2178.65     202 2167.88   260.4 2151.17
   320.5 2138.26   412.5 2123.75  428.43 2114.53   432.7  2113.2   444.8 2112.91
  454.27 2114.52     461 2116.28   473.2 2115.33   505.5 2116.63   522.7 2114.15
   537.9 2113.71   550.1 2116.14   687.7 2117.34     716 2116.21   736.2 2118.35
   748.4  2126.2   769.3 2145.73   808.6 2175.18   816.7 2178.29   832.7 2179.84
     885 2199.93  1025.6 2263.05  1041.7 2265.07  1049.7    2270  1060.5 2273.76
#Mann= 6, -1 ,  0
       0     0.1       0  428.43   0.045       0  454.27     0.1       0
  484.11    0.05       0  584.11    0.06       0  684.11     0.1       0
#XS Ineff= 2 , 0
                          687.14         2131.51
Permanent Ineff=
       F       F
Bank Sta=428.43,454.27
XS Rating Curve= 0 ,0
Exp/Cntr=0.3,0.1

Type RM Length L Ch R = 1 ,3566    ,567.1,582.4,579.1
XS GIS Cut Line= 4
2302764.54787632665155.3600645622302664.65484268665482.469662929
2302620.83797483665872.0540133062302624.59273598 666166.41511791
#Sta/Elev= 30
       0 2225.08      37 2214.35   110.8  2189.7     211 2164.57   219.4  2160.1
   231.9 2157.25   286.9 2134.62   315.7 2125.07   340.7 2119.28   344.6 2117.62
   358.2 2106.64   364.9 2105.12  373.352106.617     381 2108.17   401.1 2107.12
   457.5 2108.39   517.8 2106.86   598.5 2106.94   630.5 2108.81   715.1    2107
   735.2 2108.85   746.4 2114.02   780.4 2135.35   815.2 2150.98   827.2 2157.88
   839.2 2160.27   847.2 2166.68   922.3 2205.51   971.2 2233.41  1028.4  2269.4
#Mann= 6, -1 ,  0
       0     0.1       0   358.2   0.045       0  373.35     0.1       0
  432.02    0.05       0  632.02    0.06       0  824.06     0.1       0
#XS Ineff= 2 , 0
                          631.74         2119.14
Permanent Ineff=
       F       F
Bank Sta=358.2,373.35
XS Rating Curve= 0 ,0
Exp/Cntr=0.3,0.1

Type RM Length L Ch R = 1 ,2984    ,377.4,382.7,386.3
XS GIS Cut Line= 4
2302345.14407945 665165.944251732302227.06212039665497.781298022
2302167.42645063665804.3837910552302189.85991649666120.779358556
#Sta/Elev= 30
       0 2206.46    50.1 2191.74   125.4 2165.41   181.7 2151.58   262.4 2136.12
   334.6 2111.26     368 2102.32   408.7 2099.13   547.2 2097.91   571.7 2099.05
   583.9 2097.82  593.972093.711   612.4 2092.23  622.482093.713   627.1 2095.71
   636.9 2103.46   640.9 2105.31   661.3 2106.17   673.4  2117.2     681 2122.13
   737.2 2145.78   813.7 2181.91   821.8 2187.19   825.8 2188.87   833.8 2189.61
   837.8 2191.77     842 2195.68   958.1 2253.25   973.1 2261.32   981.8  2267.4
#Mann= 6, -1 ,  0
       0     0.1       0     220    0.05       0  522.22     0.1       0
  593.97   0.045       0  622.48    0.06       0  724.57     0.1       0
Bank Sta=593.97,622.48
XS Rating Curve= 0 ,0
Exp/Cntr(USF)=0,0
Exp/Cntr=0.3,0.1