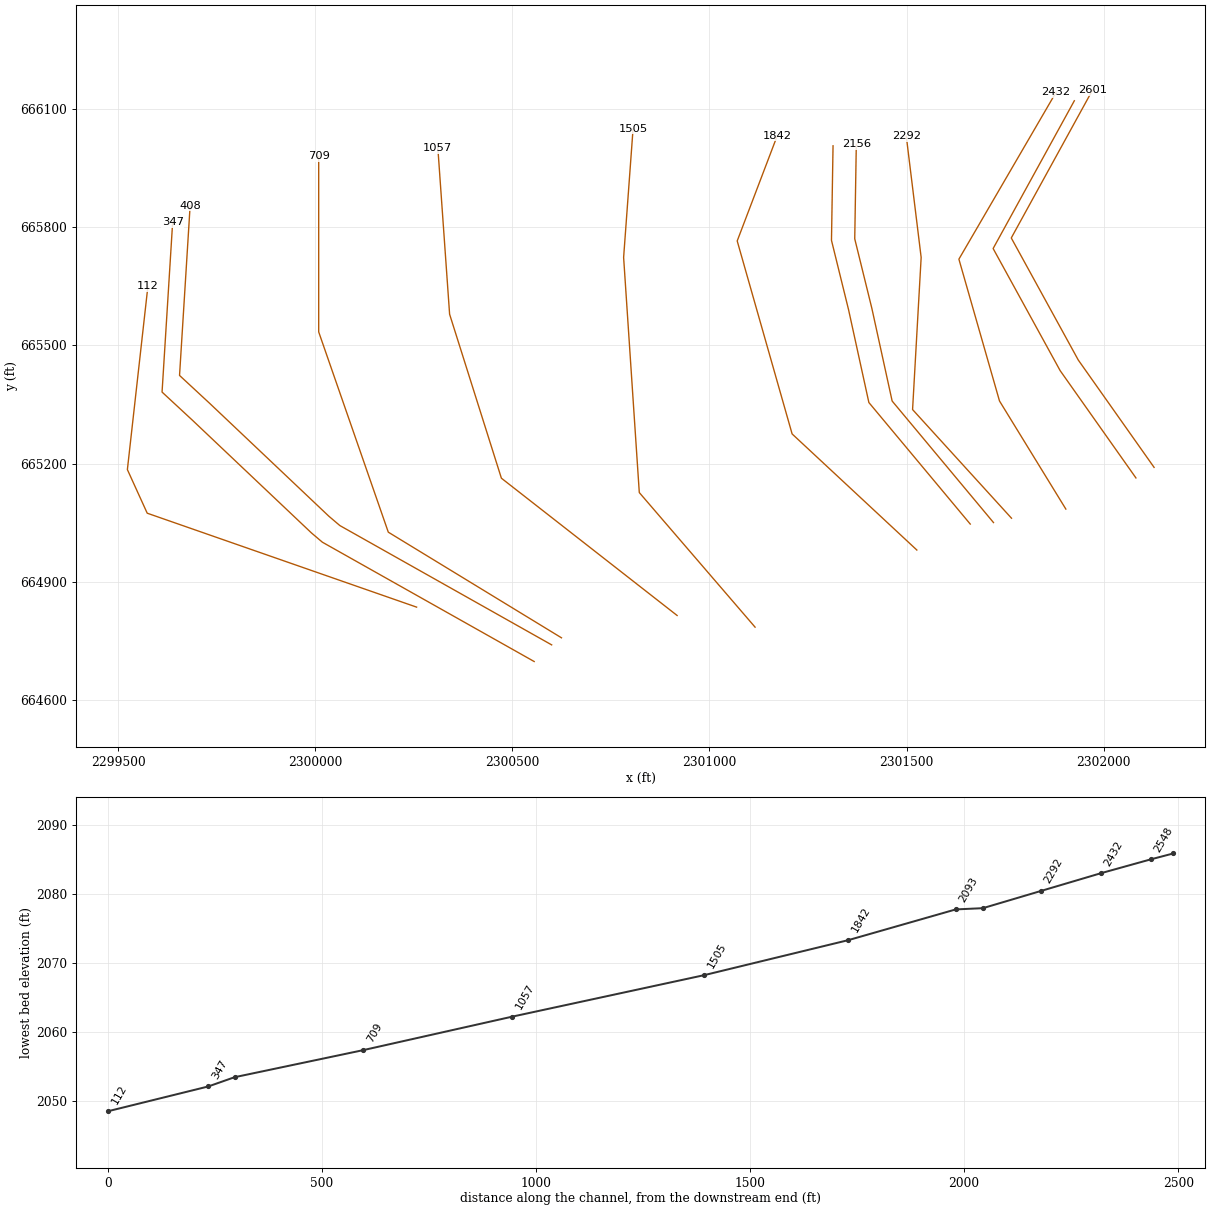
HEC-RAS study LFFILESCK.prj: LFFILESCK

--- LFFILESCK.g01 (geometry) --- (continued)

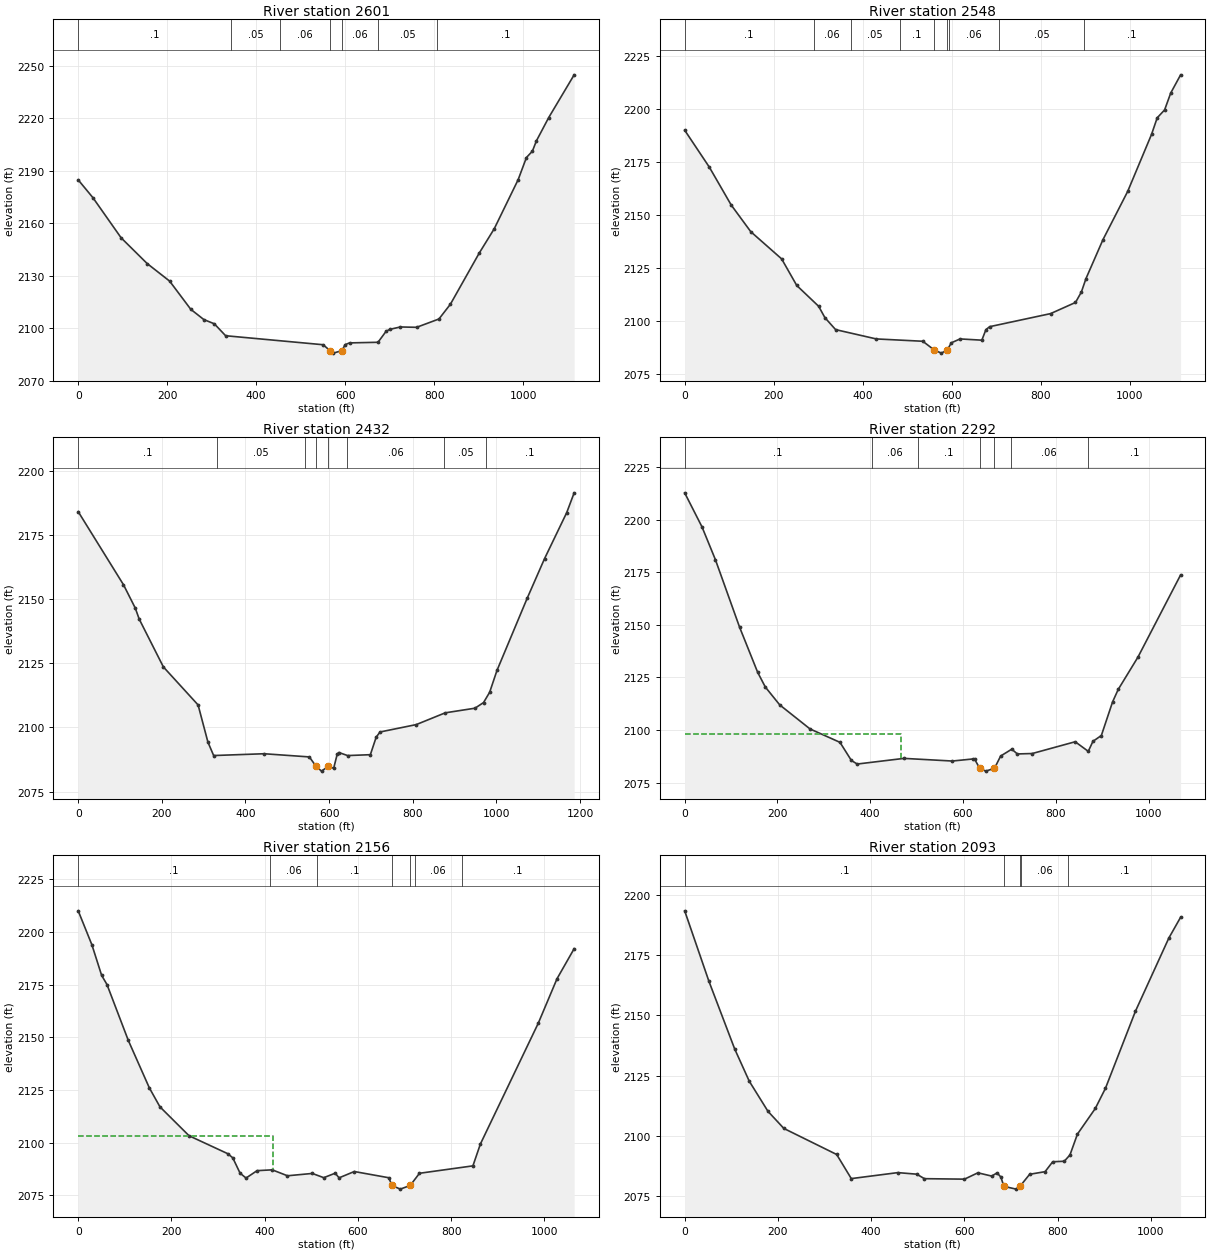
Type RM Length L Ch R = 1 ,2601    ,53.6,53.4,53.4
XS GIS Cut Line= 4
   2302127.83085665190.6265273692301935.56693826665462.870728397
2301765.56173324665772.6024319822301971.55659523666147.451973358
#Sta/Elev= 30
       0 2184.74    33.2 2174.53    96.5 2151.65   154.9    2137   205.4 2126.97
   252.9 2110.88   282.2 2105.03   305.8 2102.61   331.2  2095.8   550.4 2090.66
  565.552087.311   573.2 2085.87  592.62 2087.31   599.7 2090.71   609.7 2091.71
   673.6 2092.06   691.8 2098.34   700.3 2099.45   723.8  2100.8   760.3  2100.6
   810.5 2105.35   836.2 2113.76     901 2142.96   934.8 2156.87   988.5 2184.87
  1007.1 2197.51  1020.5 2201.14  1029.6 2207.07  1057.1 2220.29  1114.3  2244.7
#Mann= 7, -1 ,  0
       0     0.1       0  343.29    0.05       0  453.29    0.06       0
  565.55   0.045       0  592.62    0.06       0  673.29    0.05       0
  806.61     0.1       0
Bank Sta=565.55,592.62
XS Rating Curve= 0 ,0
Exp/Cntr(USF)=0,0
Exp/Cntr=0.3,0.1

Type RM Length L Ch R = 1 ,2548    ,119.4,116,112.9
XS GIS Cut Line= 4
2302081.79922711665163.8169008542301889.53531538665436.061101882
2301719.53011035665745.7928054672301925.52497235666120.642346843
#Sta/Elev= 30
       0 2190.17    55.5  2172.7   104.5 2154.88   148.5 2142.29   217.8 2129.47
   251.8 2116.92     301  2107.1   315.1 2101.73   339.1 2096.09   430.4  2091.7
     535  2090.6  560.652086.493   576.7    2085  589.912086.493   599.2 2089.88
   618.8  2091.7   667.7 2091.11   676.8 2096.07   685.3 2097.48   822.1 2103.64
   878.1  2108.9   891.3 2113.82   901.7 2120.19   939.9 2138.56   995.3 2161.26
  1048.9 2188.16  1061.7 2196.02  1078.3 2199.73  1092.1 2207.71  1114.3 2216.29
#Mann= 9, -1 ,  0
       0     0.1       0     290    0.06       0  373.29    0.05       0
  483.29     0.1       0  560.65   0.045       0  589.91     0.1       0
  593.29    0.06       0  706.61    0.05       0  896.61     0.1       0
Bank Sta=560.65,589.91
XS Rating Curve= 0 ,0
Exp/Cntr(USF)=0,0
Exp/Cntr=0.3,0.1

Type RM Length L Ch R = 1 ,2432    ,142.6,139.4,133.6
XS GIS Cut Line= 4
 2301903.9762514665084.8451046462301735.69032838  665359.0350999
2301632.68773757665718.8187973782301879.31365923666142.435086343
#Sta/Elev= 30
       0 2184.02   108.3 2155.57   136.5 2146.47   145.9 2142.18   203.7 2123.57
   286.7 2108.77   310.2  2094.3   323.9 2089.07   444.6 2089.77   552.8 2088.53
  568.862084.866   581.9    2083   597.92084.855     611 2084.13   619.4 2089.59
   623.5 2090.24   644.3 2089.06   698.7  2089.4   712.6 2096.21   721.8 2098.24
   808.5 2101.12   877.8  2105.7   948.9  2107.5   969.4  2109.7     984  2113.7
  1001.5 2122.19  1073.6 2150.25  1115.2  2165.7  1168.3 2183.65  1186.1 2191.36
#Mann= 8, -1 ,  0
       0     0.1       0  331.71    0.05       0  541.71     0.1       0
  568.86   0.045       0   597.9     0.1       0  641.71    0.06       0
  875.95    0.05       0  975.95     0.1       0
Bank Sta=568.86,597.9
XS Rating Curve= 0 ,0
Exp/Cntr(USF)=0,0
Exp/Cntr=0.3,0.1

Type RM Length L Ch R = 1 ,2292    ,128.7,136.4,140.3
XS GIS Cut Line= 4
2301766.15588341665061.6332531962301515.17773961665337.273989166
2301536.93885034665723.1710195242301499.21959174666030.728051239
#Sta/Elev= 30
       0 2212.78    37.3  2196.6    66.2 2181.02   118.4 2148.87   157.4  2127.4
   173.8 2120.45   204.9 2111.94   270.3 2100.49   334.8 2094.13   359.4 2085.51
     372 2083.81   472.8  2086.5     577 2085.24   621.1 2086.22   625.1  2086.1
  636.092081.781   649.1 2080.44  667.89 2081.78   681.2 2087.62   705.2 2090.88
   717.2 2088.61   749.3 2088.81   841.9 2094.41   870.1 2089.85   880.2 2094.61
   898.3 2097.37   922.5 2113.35   934.6 2119.26   977.2 2134.65  1069.2 2173.75
#Mann= 7, -1 ,  0
       0     0.1       0  402.78    0.06       0  502.78     0.1       0
  636.09   0.045       0  667.89     0.1       0  702.78    0.06       0
  869.29     0.1       0
#XS Ineff= 2 , 0
          466.92 2098.28
Permanent Ineff=
       F       F
Bank Sta=636.09,667.89
XS Rating Curve= 0 ,0
Exp/Cntr(USF)=0,0
Exp/Cntr=0.3,0.1

Type RM Length L Ch R = 1 ,2156    ,62.4,63.4,61.2
XS GIS Cut Line= 5
2301720.46331271665050.6288698762301463.34273074665358.909793198
2301411.89599874665593.9770648942301368.45778876665770.406001679
2301372.43285024666010.169891717
#Sta/Elev= 30
       0  2210.1    29.4 2193.93    50.2 2179.46    61.7 2175.09   107.5 2148.52
   152.5 2126.04   175.3 2117.01   237.7 2103.28     321 2094.73   331.5 2092.78
   347.1 2085.53   359.9 2083.19   383.6  2086.7   416.1 2087.09   448.8 2084.27
     502 2085.38   526.6 2083.37   551.2  2085.5   559.4 2083.29   592.1 2086.29
     666 2083.34  672.862079.678   690.7 2077.93  712.04 2079.68   731.9 2085.46
   846.5 2088.98   862.5 2099.35   986.6  2156.7  1026.9 2177.87  1063.6 2192.13
#Mann= 7, -1 ,  0
       0     0.1       0  411.43    0.06       0  511.43     0.1       0
  672.86   0.045       0  712.04     0.1       0  722.06    0.06       0
  822.06     0.1       0
#XS Ineff= 2 , 0
          416.78 2103.16
Permanent Ineff=
       F       F
Bank Sta=672.86,712.04
XS Rating Curve= 0 ,0
Exp/Cntr(USF)=0,0
Exp/Cntr=0.3,0.1

Type RM Length L Ch R = 1 ,2093    ,243.2,250.7,246.2
XS GIS Cut Line= 5
2301661.44979173665046.8215459422301404.32920977665355.102469264
2301352.88247776 665590.169740962301309.44426778665766.598677745
2301313.41932926666006.362567783
#Sta/Elev= 30
       0 2193.54      52 2164.22   107.2 2136.09   138.5 2122.66   178.7  2110.1
   212.7    2103     326 2092.16   357.3 2082.13   457.1 2084.62   497.7 2083.97
   514.1  2082.1   600.1  2081.9   628.8 2084.54   658.4 2083.18   669.9  2084.5
   678.1 2082.79  684.522078.911   710.8 2077.75  719.012078.911   739.9 2083.93
   772.9 2085.01   789.3 2089.14   814.1 2089.35   826.3 2091.98   842.3 2100.64
   880.6  2111.3   902.4  2119.7   966.7 2151.76  1038.4 2182.24  1063.6 2190.87
#Mann= 5, -1 ,  0
       0     0.1       0  684.52   0.045       0  719.01     0.1       0
  722.06    0.06       0  822.06     0.1       0
Bank Sta=684.52,719.01
XS Rating Curve= 0 ,0
Exp/Cntr(USF)=0,0
Exp/Cntr=0.3,0.1

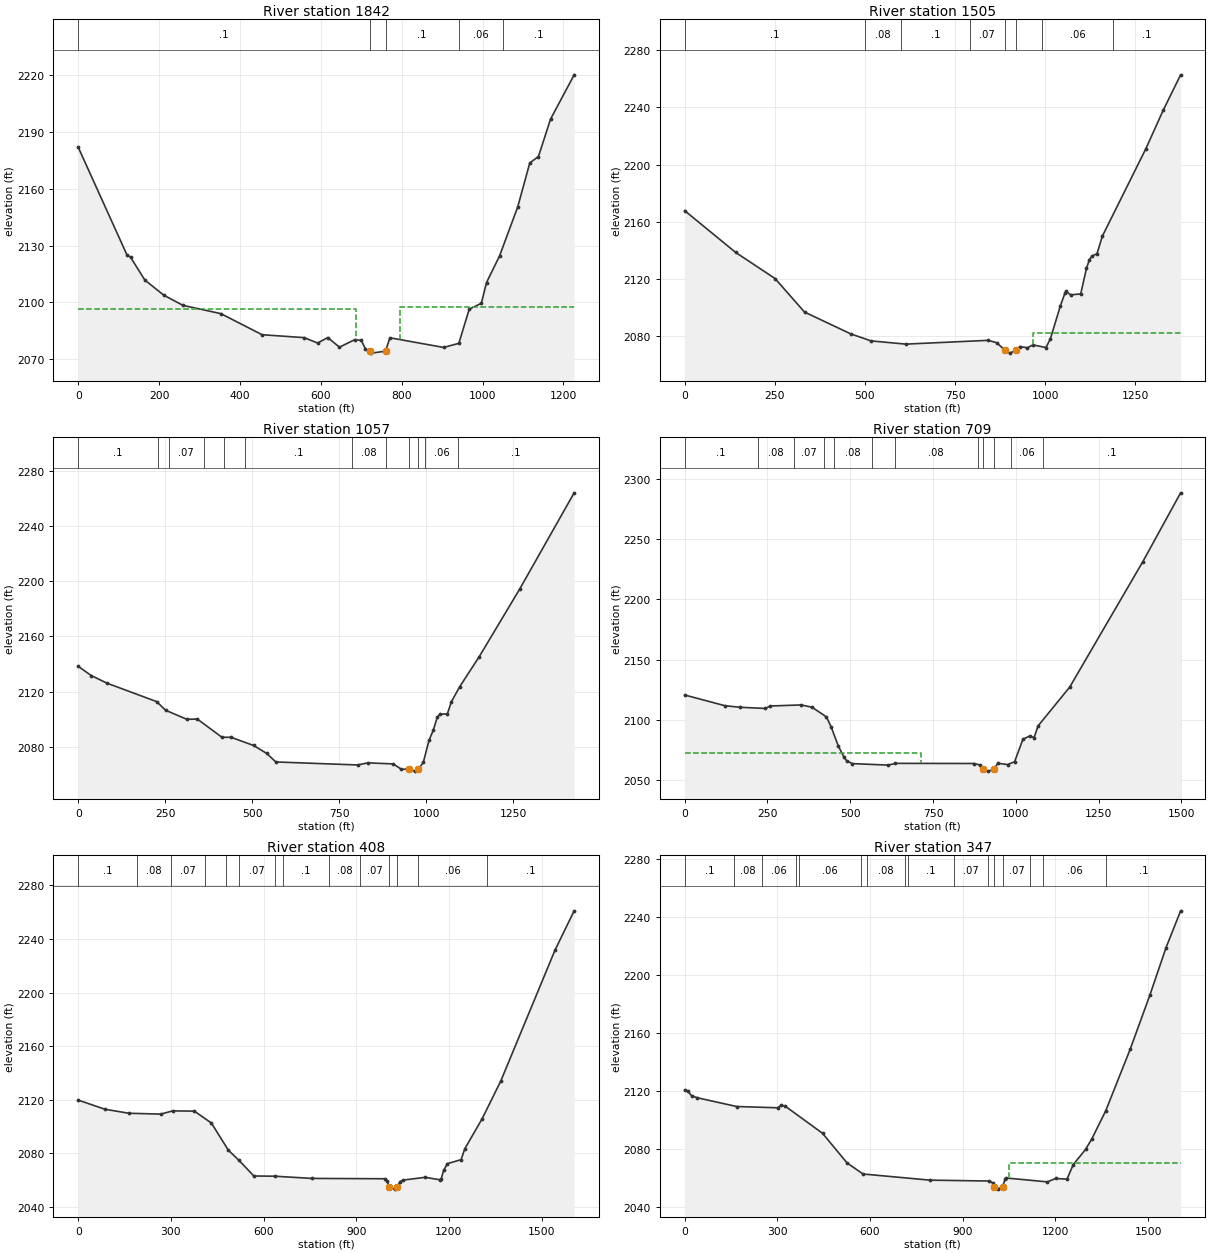
Type RM Length L Ch R = 1 ,1842    ,341.3,336.9,331.8
XS GIS Cut Line= 4
2301526.01249393664980.9316709972301209.59579464665275.457906819
2301070.29284526665765.0082717652301171.78499409666031.673917712
#Sta/Elev= 30
       0 2181.82   120.3 2125.19   129.5 2123.81   164.7 2111.84   211.7 2103.83
     259 2098.48   352.6 2094.12   454.9    2083   558.8 2081.47   592.1 2078.62
   617.1 2081.49   646.2 2076.44   683.6 2080.38   700.2 2080.03     710 2075.68
  720.582074.333   725.2  2073.3  760.062074.334   770.9 2081.39     904 2076.29
   941.4 2078.47   967.1 2096.47   997.1 2099.56  1009.9 2110.52  1042.1 2124.53
    1087 2150.34  1116.9 2173.57  1138.3 2176.92  1168.3 2196.68  1226.6 2219.98
#Mann= 5, -1 ,  0
       0     0.1       0  720.58   0.045       0  760.06     0.1       0
  941.26    0.06       0 1051.26     0.1       0
#XS Ineff= 2 , 0
          687.17 2096.63  795.03         2097.69
Permanent Ineff=
       F       F
Bank Sta=720.58,760.06
XS Rating Curve= 0 ,0
Exp/Cntr(USF)=0,0
Exp/Cntr=0.3,0.1

Type RM Length L Ch R = 1 ,1505    ,443.8,448.7,450.4
XS GIS Cut Line= 4
2301115.62671595664785.3115320182300821.91655302665126.697689367
2300782.16075641 665723.307189242300806.11649664 666049.50597138
#Sta/Elev= 30
       0  2167.8   141.3 2138.62   250.6 2120.36   332.3 2096.94   460.8 2081.65
     517 2076.77   613.2 2074.52   841.7 2077.16   865.7 2075.46  887.892070.246
   901.8 2068.22  918.092070.247   929.9 2072.83   949.9 2071.95     966 2073.96
    1002 2072.14  1014.1 2078.16  1042.1 2101.39  1054.2 2109.95  1058.2 2111.35
  1070.2 2108.96  1098.3 2109.58  1114.3 2127.44  1122.3  2133.5  1130.4 2136.22
  1143.4 2137.67  1158.4 2150.01  1278.8    2211  1326.9 2237.87  1375.4 2262.75
#Mann= 8, -1 ,  0
       0     0.1       0  500.34    0.08       0  600.34     0.1       0
  790.34    0.07       0  887.89   0.045       0  918.09     0.1       0
  990.34    0.06       0 1188.28     0.1       0
#XS Ineff= 2 , 0
                          966.31         2082.42
Permanent Ineff=
       F       F
Bank Sta=887.89,918.09
XS Rating Curve= 0 ,0
Exp/Cntr(USF)=0,0
Exp/Cntr=0.3,0.1

Type RM Length L Ch R = 1 ,1057    ,344.3,347.7,343.6
XS GIS Cut Line= 4
2300917.84259349664814.8979064652300472.07315548665163.155279903
2300340.73037465665579.0740858962300310.87974264 666000.96301829
#Sta/Elev= 30
       0  2138.3    37.6 2131.58    83.3 2126.01   225.5 2112.66   250.8 2106.46
   311.8 2099.83   342.2 2100.02     413 2086.77     439 2086.78     504 2080.81
   541.4 2075.08   567.8 2068.86   802.7 2066.68   832.1  2068.2   905.1 2067.43
   928.5 2063.53   950.6 2063.68   966.3  2062.2  977.562063.675   991.5 2068.62
  1007.8  2084.5    1020 2091.89    1032 2101.68    1040 2103.57  1060.5 2103.75
  1072.1  2112.6  1096.2 2123.58  1152.3 2145.41  1268.6 2194.53  1424.8 2264.29
#Mann= 12, -1 ,  0
       0     0.1       0     230    0.08       0     260    0.07       0
     360    0.06       0     420    0.08       0     480     0.1       0
  785.68    0.08       0  885.68    0.07       0   950.6   0.045       0
  977.56    0.07       0  995.68    0.06       0 1091.84     0.1       0
Bank Sta=950.6,977.56
XS Rating Curve= 0 ,0
Exp/Cntr(USF)=0,0
Exp/Cntr=0.3,0.1

Type RM Length L Ch R = 1 ,709     ,295.3,300.8,306.7
XS GIS Cut Line= 4
2300624.47327617664758.2781139792300185.18605821665026.239402485
2300008.62941633665534.1851997052300008.63269097665979.580517173
#Sta/Elev= 30
       0 2120.58   121.6 2111.68   166.9 2110.39   243.7  2109.4   258.4 2111.44
   351.6 2112.34   384.6 2110.41     428 2102.41   441.8 2094.41   464.2 2078.07
   481.8 2068.67   489.5 2065.81   506.4  2063.6   615.1 2062.35   636.2  2063.8
   873.4 2063.68   891.6 2062.51  901.462058.941   915.7 2057.35  934.812058.938
   945.4 2063.91     975 2062.79   996.2  2065.1  1021.6 2083.92  1041.5 2086.43
  1055.3 2085.27  1067.3 2094.93  1162.9  2127.2  1383.8 2231.43  1497.7 2288.48
#Mann= 12, -1 ,  0
       0     0.1       0     220    0.08       0     330    0.07       0
     420    0.06       0     450    0.08       0  564.56     0.1       0
  634.56    0.08       0  884.56     0.1       0  901.46   0.045       0
  934.81     0.1       0  984.56    0.06       0 1082.32     0.1       0
#XS Ineff= 2 , 0
          714.43 2072.77
Permanent Ineff=
       F       F
Bank Sta=901.46,934.81
XS Rating Curve= 0 ,0
Exp/Cntr(USF)=0,0
Exp/Cntr=0.3,0.1

Type RM Length L Ch R = 1 ,408     ,61.3,61.4,61.2
XS GIS Cut Line= 6
2300599.59008959664740.3419920472300062.27871343665043.027400618
2300034.37058324  665066.72854932299732.60643809665352.479194685
2299655.60604327665423.8591227222299682.48006342665854.482231621
#Sta/Elev= 30
       0  2119.8    86.6 2112.97   164.5 2109.97   267.4 2109.38   305.6 2111.75
   375.8 2111.59   430.9 2102.77     486 2082.45     520 2074.97   568.6 2063.22
   636.7 2063.05   755.6 2061.41     992 2061.16  1000.5 2059.16 1007.662054.719
  1024.4 2053.42 1033.132054.721  1041.4 2058.97  1052.9 2060.18  1123.5 2062.24
    1170  2060.4  1175.2 2061.33  1183.2 2067.56  1195.3 2072.44  1239.4 2075.39
  1251.4 2083.54  1307.5 2105.88  1368.1 2134.15  1543.9 2231.87  1605.4 2260.93
#Mann= 14, -1 ,  0
       0     0.1       0     190    0.08       0     300    0.07       0
     410    0.06       0     480    0.08       0     520    0.07       0
   636.7    0.08       0  663.32     0.1       0  812.21    0.08       0
  912.21    0.07       0 1007.66   0.045       0 1033.13    0.07       0
 1098.91    0.06       0 1323.91     0.1       0
Bank Sta=1007.66,1033.13
XS Rating Curve= 0 ,0
Exp/Cntr(USF)=0,0
Exp/Cntr=0.3,0.1

Type RM Length L Ch R = 1 ,347     ,237.6,234.1,226
XS GIS Cut Line= 6
2300555.24142857664698.1178177872300017.93005241665000.803226358
2299990.02192222 665024.504375042299688.25777707665310.255020424
2299611.25738226665381.634948462 2299638.1314024 665812.25805736
#Sta/Elev= 30
       0 2120.51    10.4 2119.56    22.1 2116.53    40.2 2115.11   168.2 2109.05
   301.1 2108.17   312.9 2109.94   324.9 2109.38   446.3 2090.56   525.7 2070.13
   577.4 2062.51   793.7 2058.28   986.2 2057.67   997.5 2056.39 1002.372053.828
  1013.7 2052.08 1029.242053.827  1037.1 2058.86  1041.3 2059.75  1173.9 2057.09
  1200.8 2059.42  1237.6 2058.97  1257.6 2068.88  1297.7 2079.47  1317.8 2086.65
    1363  2106.1    1442 2148.45  1505.9 2185.87  1558.2  2218.6  1605.4 2243.97
#Mann= 16, -1 ,  0
       0     0.1       0     160    0.08       0     250    0.06       0
     360    0.07       0     370    0.06       0     570    0.07       0
     590    0.08       0  713.32    0.06       0  723.32     0.1       0
  872.21    0.07       0   982.9     0.1       0 1002.37   0.045       0
 1029.24    0.07       0 1118.91    0.05       0 1158.91    0.06       0
 1363.91     0.1       0
#XS Ineff= 2 , 0
                         1050.03         2070.19
Permanent Ineff=
       F       F
Bank Sta=1002.37,1029.24
XS Rating Curve= 0 ,0
Exp/Cntr(USF)=0,0
Exp/Cntr=0.3,0.1

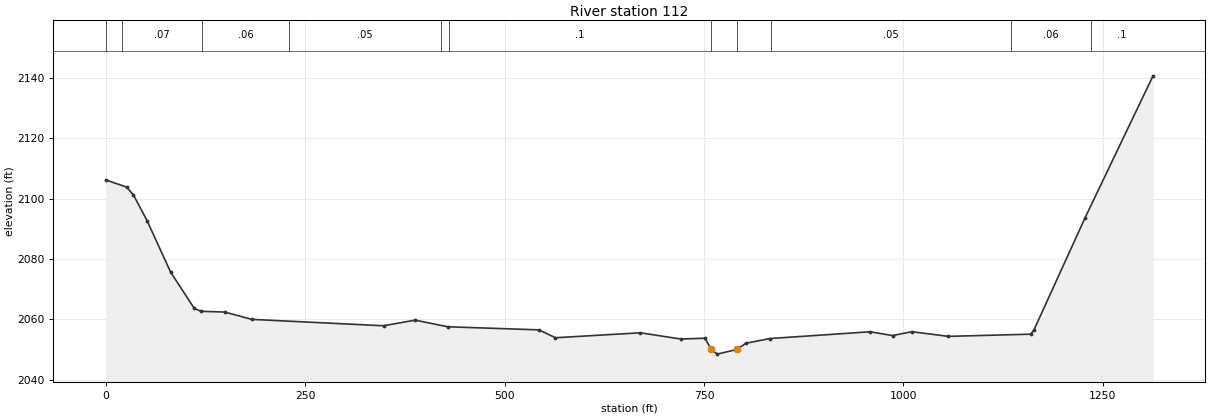
Type RM Length L Ch R = 1 ,112     ,,,
XS GIS Cut Line= 4
2300256.98025004664836.0821386072299573.60230992665074.379958947
2299523.28061317665185.0022689872299575.32183833665649.733528801
#Sta/Elev= 30
       0 2106.22    26.3 2103.85    34.7 2101.25    51.9 2092.65    81.3 2075.66
     111 2063.63   119.5 2062.68   149.1 2062.44     183 2060.01   348.2 2057.89
   387.8 2059.76   428.7 2057.56   543.1 2056.53   563.7 2053.92   670.2 2055.56
   720.8  2053.5   751.1 2053.76  758.922050.174   766.4 2048.49791.06982050.042
   802.4 2052.09   832.3 2053.65   958.1  2055.9   986.3 2054.65  1010.5 2055.92
  1056.2 2054.38  1159.4  2055.1  1163.4  2056.4  1227.8 2093.75  1312.9 2140.74
#Mann= 11, -1 ,  0
       0    0.06       0      20    0.07       0     120    0.06       0
     230    0.05       0     420    0.06       0     430     0.1       0
  758.92   0.045       0791.0698     0.1       0  833.73    0.05       0
 1135.26    0.06       0 1235.26     0.1       0
Bank Sta=758.92,791.0698
XS Rating Curve= 0 ,0
Exp/Cntr=0.3,0.1
LCMann Table=0

Chan Stop Cuts=-1
Use User Specified Reach Order=0
Composite Channel Slope=5